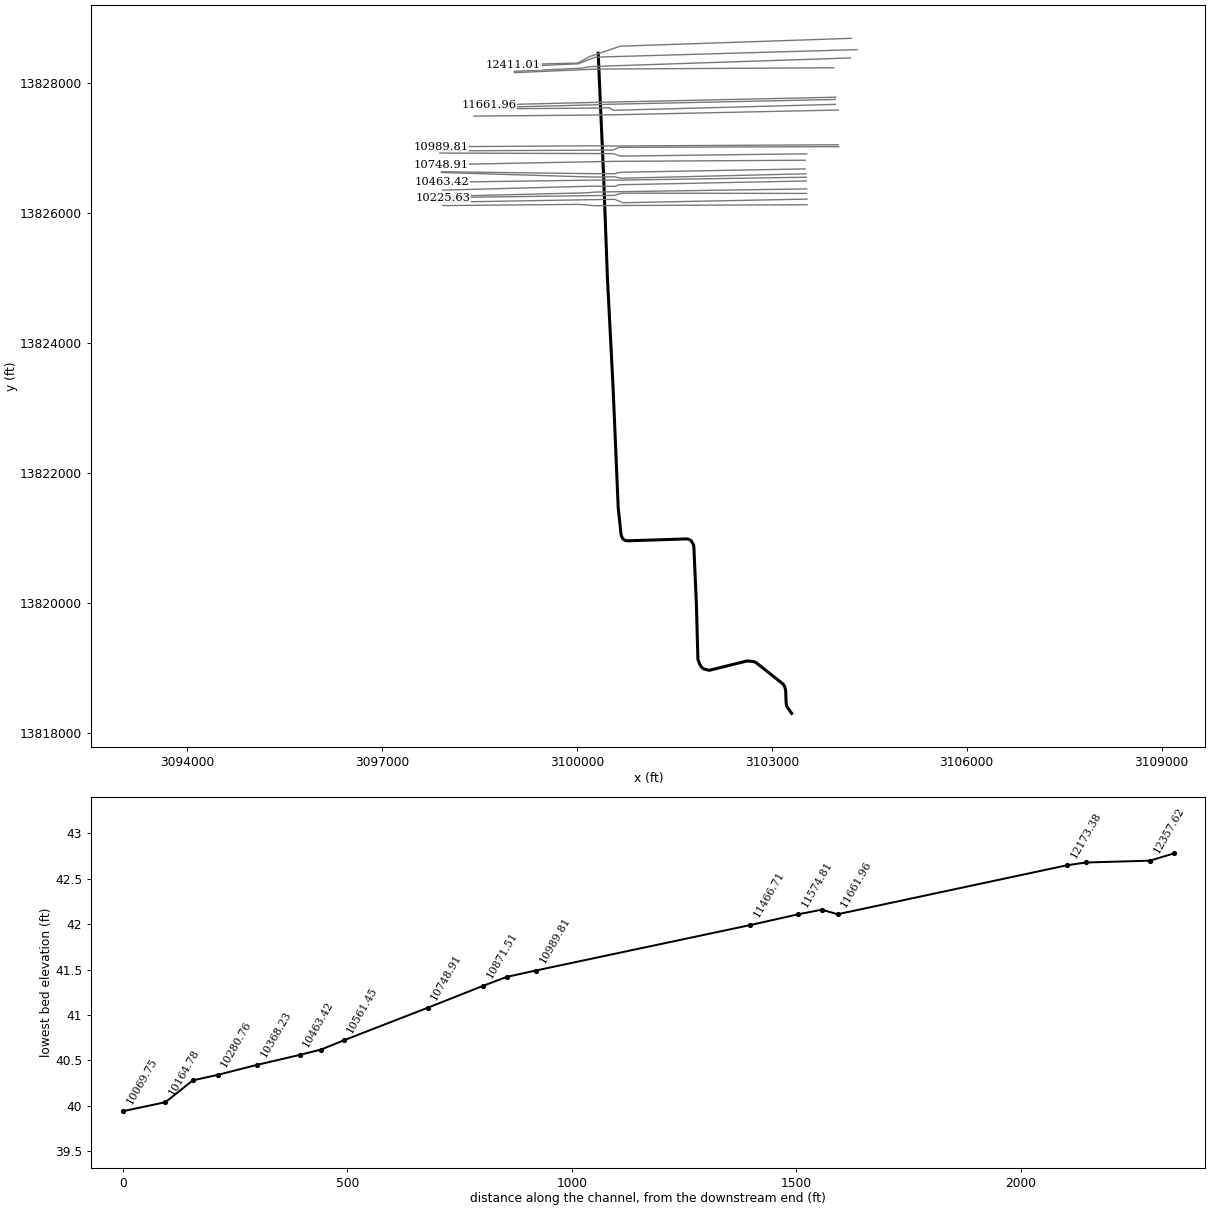
--- D111-00-00.prj (project) ---

Proj Title=D111-00-00
Current Plan=p01
Default Exp/Contr=.3,.1
English Units
Geom File=g01
Flow File=f02
Flow File=f01
Plan File=p02
Plan File=p01
Y Axis Title=Elevation
X Axis Title(PF)=Main Channel Distance
X Axis Title(XS)=Station
BEGIN DESCRIPTION:
HCFCD MODEL SUMMARY METADATA
The purpose of this summary is to document the high points of hydrologic and hydraulic models filed within the HCFCD Model and Map Management (M3) system.  The document includes references to the project that prompted the creation or update of the model.
DESCRIPTION OF PROJECT:
The following model was the hydraulic model which represented the effective condition of Harris County's watersheds.
PURPOSE OF PROJECT:
Development of effective models to support the National Flood Insurance Program.
HCFCD Watershed Unit ID: D
M3 Study Identifier: 2007_Effective_D
Engineer: HCFCD
Project Name: EffectiveFEMA Study for watershed Brays Bayou (D)
Study Completion Date: 6/18/2007
FEMA Case Number: [No Data]
FEMA Approval Date: [No Date in Database]
Vertical Datum: NAVD 1988
Datum Note: 2001 ADJ
HYDRAULICS
HCFCD Unit No.:  D111-00-00
Hydraulic Program Name: HEC-RAS
Hydraulic Program Version: 3.0.1
Steady Hydraulic Model: Yes
Unsteady Hydraulic Model: No
Update 1:
The effective FEMA hydraulic model for unit number D111-00-00 has been updated by FEMA LOMR 12-06-3459P with an effective date of 03/04/2013.
END DESCRIPTION:
DSS Export Rating Curves= 0
DSS Export Rating Curve Sorted= 0
DSS Export Volume Flow Curves= 0
DXF OffsetX= 0
DXF OffsetY= 0
DXF ScaleX= 1
DXF ScaleY= 10

--- D111-00-00.p01 (plan) ---

Plan Title=Effective Multi-Profile 2013
Version=Version 3.0.1  May 2012
Short Identifier=Eff+LOMR MP
Geom File=g01
Flow File=f01
Subcritical Flow
K Sum by GR= 0
Std Step Tol= 0.01
Critical Tol= 0.01
Num of Std Step Trials= 20
Max Error Tol= 0.3
Flow Tol Ratio= 0.001
Split Flow NTrial= 30
Split Flow Tol= 0.02
Split Flow Ratio= 0.02
Log Output Level= 0
Friction Slope Method= 0
Unsteady Friction Slope Method= 2
Secant Critical Depth
Global Vel Dist= 0 , 0 , 0
Global Log Level= 0
CheckData=False
Encroach Param=-1 ,0,0, 2
BEGIN DESCRIPTION:
FEMA Effective Multi-Profile June 2007 + LOMR 12-06-3459P
END DESCRIPTION:
Computation Interval=1HOUR
Output Interval=1HOUR
Run HTab= 0
Run UNet= 0
Run PostProcess= 0
UNET Theta= 1
UNET ZTol= 0.02
UNET ZSATol= 0.1
UNET MxIter= 20
UNET MaxInSteps= 20
UNET DtIC= 0
UNET DtMin= 0
UNET MaxCRTS= 20
UNET WFStab= 2
UNET SFStab= 1
UNET WFX= 1
UNET SFX= 1
UNET Convert EG Bridges=-1
UNET Use Existing IB Tables=-1
Instantaneous Interval=1HOUR
Write IC File= 0
IC Time=0
Write Velocity= 0
Write Detailed= 0

--- D111-00-00.p02 (plan) ---

Plan Title=Effective Floodway 2013
Version=Version 3.0.1  May 2012
Short Identifier=Eff FW+LOMR
Geom File=g01
Flow File=f02
Subcritical Flow
K Sum by GR= 0
Std Step Tol= 0.01
Critical Tol= 0.01
Num of Std Step Trials= 20
Max Error Tol= 0.3
Flow Tol Ratio= 0.001
Split Flow NTrial= 30
Split Flow Tol= 0.02
Split Flow Ratio= 0.02
Log Output Level= 0
Friction Slope Method= 0
Unsteady Friction Slope Method= 2
Secant Critical Depth
Global Vel Dist= 0 , 0 , 0
Global Log Level= 0
CheckData=False
Encroach Param=-1 ,0,0, 2
Encroach River=D111
Encroach Reach=D111-00-00_0001
Encroach Node=12411.01
       1 3892.32 3932.67
Encroach Node=12357.62
       1  3964.6 3993.07
Encroach Node=12215.95
       1 3861.46 3899.19
Encroach Node=12173.38
       1 3585.17    3634
Encroach Node=11661.96
       1 3595.28    3633
Encroach Node=11626.60
       1 3594.04 3652.13
Encroach Node=11600
       1 3593.62  3653.2
Encroach Node=11574.81
       1 3593.62  3653.2
Encroach Node=11466.71
       1 3630.94 3670.65
Encroach Node=10989.81
       1 3603.28 3643.44
Encroach Node=10924.99
       1  3618.1 3675.25
Encroach Node=10900
       1
Encroach Node=10871.51
       1 3130.65 3163.19
Encroach Node=10748.91
       1 3095.76 3129.99
Encroach Node=10561.45
       1 3091.78 3121.99
Encroach Node=10511.71
       1    3078 3154.21
Encroach Node=10500
       1
Encroach Node=10463.42
       1    3102 3140.05
Encroach Node=10368.23
       1 3087.39 3148.74
Encroach Node=10280.76
       1 3103.01 3135.45
Encroach Node=10225.63
       1  3093.3 3129.98
Encroach Node=10200
       1
Encroach Node=10164.78
       1 3107.79    3150
Encroach Node=10069.75
       1 3090.33 3142.53
Encroach Node=9511.942
       1    3085 3133.33
Encroach Node=9463.775
       1    3120    3170
Encroach Node=9450
       1
Encroach Node=9411.652
       1    3141    3190
Encroach Node=9307.397
       1 3128.92 3170.76
Encroach Node=8805.521
       1 2703.23 2733.43
Encroach Node=8752.369
       1 2673.14 2742.86
Encroach Node=8677
       1
Encroach Node=8674.259
       1 2669.39 2745.47
Encroach Node=8645.981
       1 2673.17 2753.84
Encroach Node=7730.220
       1 2699.92 2749.56
Encroach Node=6656.935
       1 2707.25 2790.59
Encroach Node=5588.431
       1 3861.96 3916.72
Encroach Node=5540.284
       1 3840.19 3890.23
Encroach Node=5430
       1
Encroach Node=5426.389
       1    3839    3917
Encroach Node=5319.974
       1  3862.1 3913.02
Encroach Node=5031.747
       1  114.73  203.38
Encroach Node=4984.889
       1  119.12   195.9
Encroach Node=4921.495
       1   91.49  196.42
Encroach Node=4738.757
       1   67.24  145.97
Encroach Node=4394.391
       1   73.21  155.68
Encroach Node=4348.580
       1   68.26  143.84
Encroach Node=4330
       1
Encroach Node=4317.548
       1   67.46  155.65
Encroach Node=4223.081
       1   61.82  166.99
Encroach Node=3920.974
       1   78.02  221.77
Encroach Node=3739.383
       1  108.22  197.98
Encroach Node=3484.569
       1  110.79  214.39
Encroach Node=3381.998
       1  116.27  206.28
Encroach Node=3350
       1
Encroach Node=3333.050
       1  114.25  207.43
Encroach Node=3234.850
       1   112.3  212.46
Encroach Node=2862.337
       1   93.42  228.42
Encroach Node=2793.765
       1  105.68  199.11
Encroach Node=2750
       1
Encroach Node=2743.431
       1  106.03  195.98
Encroach Node=2593.610
       1  121.46  210.97
Encroach Node=2088.410
       1  123.54  224.15
Encroach Node=1673.719
       1   74.13  176.51
Encroach Node=1337.589
       1   86.93  174.71
Encroach Node=1287.091
       1   53.11   158.2
Encroach Node=1250
       1
Encroach Node=1204.789
       1   34.77  134.57
Encroach Node=1104.982
       1   28.61  151.43
Encroach Node=892.759
       1   91.46  208.03
Encroach Node=485.205
       1   73.39  192.15
Encroach Node=311.156
       1  112.38  232.38
Encroach Node=257.119
       1  124.94  232.84
Encroach Node=200
       1
Encroach Node=147.878
       1  124.94  228.34
Encroach Node=51.269
       1     120     250
BEGIN DESCRIPTION:
FEMA Effective Floodway June 2007 + LOMR 12-06-3459P
END DESCRIPTION:
Computation Interval=1HOUR
Output Interval=1HOUR
Run HTab= 0
Run UNet= 0
Run PostProcess= 0
UNET Theta= 1
UNET ZTol= 0.02
UNET ZSATol= 0.1
UNET MxIter= 20
UNET MaxInSteps= 20
UNET DtIC= 0
UNET DtMin= 0
UNET MaxCRTS= 20
UNET WFStab= 2
UNET SFStab= 1
UNET WFX= 1
UNET SFX= 1
UNET Convert EG Bridges=-1
UNET Use Existing IB Tables=-1
Instantaneous Interval=1HOUR
Write IC File= 0
IC Time=0
Write Velocity= 0
Write Detailed= 0

--- D111-00-00.f01 (steady flow) ---

Flow Title=Effective Multi-Profile 2013
Version=Version 3.0.1  Mar 2001
Number of Profiles= 4
Profile Names=10PCT_10yr,2PCT_50yr,1PCT_100yr,0.2PCT_500yr
River Rch & RM=D111,D111-00-00_0001 ,12411.01
   219.8   318.1   367.6   503.9
River Rch & RM=D111,D111-00-00_0001 ,11661.96
   304.7     441   508.7   699.3
River Rch & RM=D111,D111-00-00_0001 ,10989.81
   389.5   563.9   651.1   894.7
River Rch & RM=D111,D111-00-00_0001 ,10368.23
   468.8   677.2   782.7  1074.2
River Rch & RM=D111,D111-00-00_0001 ,9511.942
   570.4     826   953.6  1310.9
River Rch & RM=D111,D111-00-00_0001 ,8645.981
   674.7   974.9  1125.9  1547.5
River Rch & RM=D111,D111-00-00_0001 ,7730.220
   779.1  1126.4  1300.9  1786.8
River Rch & RM=D111,D111-00-00_0001 ,6656.935
   898.7  1299.8  1501.6  2063.4
River Rch & RM=D111,D111-00-00_0001 ,5588.431
  1048.9  1516.9  1751.2  2407.7
River Rch & RM=D111,D111-00-00_0001 ,5031.747
  1122.7  1624.8    1876  2577.9
River Rch & RM=D111,D111-00-00_0001 ,3234.850
  1185.3  1713.5  1979.1  2718.8
River Rch & RM=D111,D111-00-00_0001 ,1337.589
  1245.1  1799.5  2078.1  2855.7
River Rch & RM=D111,D111-00-00_0001 ,51.269
  1260.4  1822.7  2105.2  2892.9
Boundary for River Rch & Prof#=D111,D111-00-00_0001 , 1
Up Type= 0
Dn Type= 3
Dn Slope=.0004
DSS Import GetInterval= 0
DSS Import GetPeak= 0
DSS Import FillOption= 0

--- D111-00-00.f02 (steady flow) ---

Flow Title=Effective Floodway 2013
Version=Version 3.0.1  Mar 2001
Number of Profiles= 2
Profile Names=1PCT_100yr,1PCTFloodway_100yr
River Rch & RM=D111,D111-00-00_0001 ,12411.01
   367.6   367.6
River Rch & RM=D111,D111-00-00_0001 ,11661.96
   508.7   508.7
River Rch & RM=D111,D111-00-00_0001 ,10989.81
   651.1   651.1
River Rch & RM=D111,D111-00-00_0001 ,10368.23
   782.7   782.7
River Rch & RM=D111,D111-00-00_0001 ,9511.942
   953.6   953.6
River Rch & RM=D111,D111-00-00_0001 ,8645.981
  1125.9  1125.9
River Rch & RM=D111,D111-00-00_0001 ,7730.220
  1300.9  1300.9
River Rch & RM=D111,D111-00-00_0001 ,6656.935
  1501.6  1501.6
River Rch & RM=D111,D111-00-00_0001 ,5588.431
  1751.2  1751.2
River Rch & RM=D111,D111-00-00_0001 ,5031.747
    1876    1876
River Rch & RM=D111,D111-00-00_0001 ,3234.850
  1979.1  1979.1
River Rch & RM=D111,D111-00-00_0001 ,1337.589
  2078.1  2078.1
River Rch & RM=D111,D111-00-00_0001 ,51.269
  2105.2  2105.2
Boundary for River Rch & Prof#=D111,D111-00-00_0001 , 1
Up Type= 0
Dn Type= 3
Dn Slope=.0004
DSS Import GetInterval= 0
DSS Import GetPeak= 0
DSS Import FillOption= 0

--- D111-00-00.g01 (geometry) ---

Geom Title=D111-00-00 June 2007
Version=Version 3.0.1  Mar 2001

River Reach=D111            ,D111-00-00_0001
Reach XY= 30
      3100327.85    13828460.837     3100414.932    13826478.565
     3100469.956    13825001.586     3100556.033    13823335.101
     3100635.907    13821468.546     3100679.721    13821051.344
     3100692.583     13821011.71     3100714.617       13820980.
     3100747.187    13820959.838     3100781.307    13820955.961
     3101692.096    13820985.429     3101724.666    13820977.674
     3101757.358    13820959.221     3101795.621    13820893.923
     3101800.274    13820860.578     3101839.048    13819988.175
     3101862.711    13819130.358     3101894.204    13819049.375
     3101922.411    13819007.206      3101954.98    13818982.391
     3102034.854    13818962.229     3102616.844    13819106.466
     3102719.981    13819097.936     3102760.306    13819079.324
     3103174.794    13818750.525     3103197.283    13818715.629
      3103213.55    13818650.459     3103220.159    13818465.153
     3103228.689    13818408.543     3103305.461    13818299.978

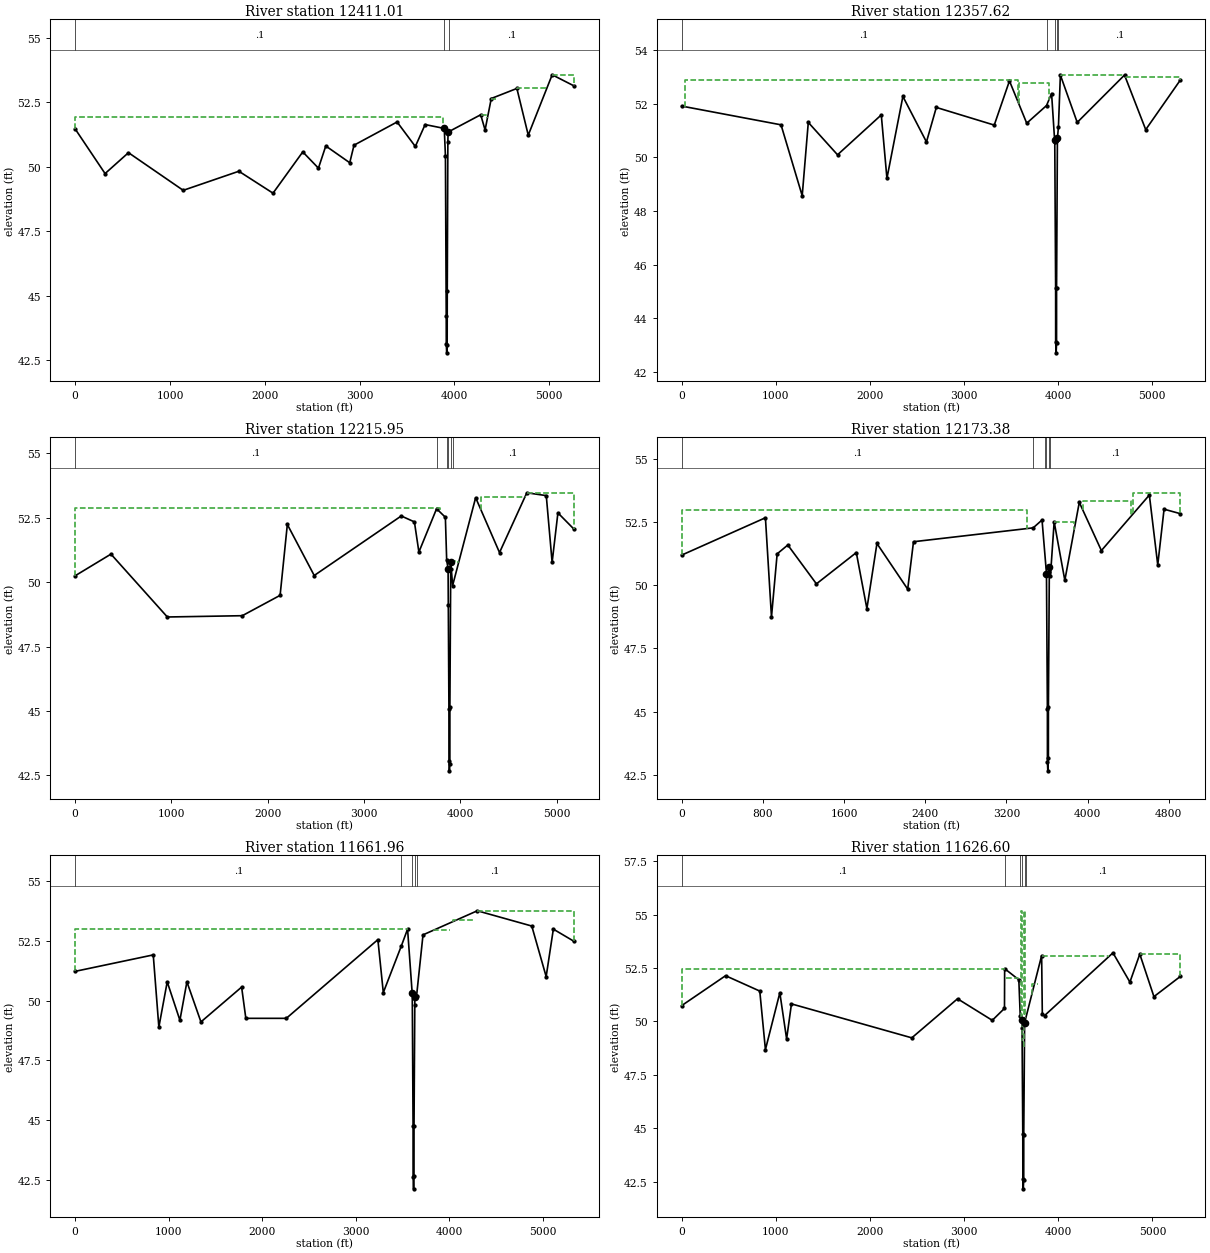
Type RM Length L Ch R = 1 ,12411.01,67.52,53.38,44.54
BEGIN DESCRIPTION:
Survey Data Used for Points from Station 130.20 to 159.86.
.  All other Points obtained from LIDAR data.
END DESCRIPTION:
XS GIS Cut Line= 6
     3104228.388    13828689.597     3100669.285    13828568.941
     3100467.754    13828500.853     3100198.157    13828409.724
     3100014.989    13828309.092     3099022.847    13828284.683
#Sta/Elev= 30
       0   51.46  315.34   49.73  562.12   50.54 1139.49   49.08  1726.3   49.82
 2086.36   48.97 2400.21   50.57 2565.31   49.94 2642.88    50.8 2895.49   50.15
 2940.52   50.83 3394.78   51.73 3587.25   50.78 3690.37   51.63 3892.32   51.48
 3904.61   50.42 3913.06    44.2  3913.5   43.13    3918   42.78 3922.88   43.09
 3923.97   45.19 3930.25   50.97 3932.67   51.34  4276.6   52.01 4322.74   51.42
 4387.91   52.64 4657.99   53.03 4778.03   51.22 5030.36   53.56 5259.89   53.13
#Mann= 3 ,-1 , 0
       0      .1       0 3892.32    .015       0 3944.91      .1       0
#XS Ineff= 5 ,-1
 -148.75 3877.72   51.92 4276.57 4348.17   52.01 4387.19 4433.97   52.64
 4656.36 4977.32   53.03 5030.76 5326.68   53.56
Permanent Ineff=
       F       F       F       F       F
Bank Sta=3892.32,3932.67
XS Rating Curve= 0
Exp/Cntr=.3,.1

Type RM Length L Ch R = 1 ,12357.62,141.78,141.68,164.59
XS GIS Cut Line= 6
     3104309.704    13828515.348     3100434.717    13828404.478
      3100374.23    13828402.074     3100278.563    13828398.272
     3100017.793    13828297.505      3099030.54    13828253.912
#Sta/Elev= 30
       0   51.92 1055.58   51.22 1280.67   48.57 1345.34   51.31 1656.03    50.1
 2121.01   51.59 2181.04   49.22 2350.57   52.28 2601.21   50.58 2705.88   51.87
 3321.51   51.21 3483.15   52.86 3666.65   51.28    3877   51.94 3930.85   52.39
 3964.52   50.57  3964.6   50.64 3973.87   45.12 3974.19   43.11 3979.16    42.7
 3983.66   43.06 3983.91   45.14 3992.65   50.65 3993.07   50.72 4003.58   51.14
 4024.27   53.08 4203.32   51.31 4706.03   53.08 4931.25   51.04 5300.63    52.9
#Mann= 5 ,-1 , 0
       0      .1       0    3877      .1       0 3964.52    .015       0
 3992.65     .08       0 4003.58      .1       0
#XS Ineff= 4 ,-1
   34.31 3573.06   52.89 3584.36 3901.12   52.77 4029.66 4703.76   53.09
 4716.96 5324.17   52.99
Permanent Ineff=
       F       F       F       F
Bank Sta=3964.6,3993.07
XS Rating Curve= 0
Exp/Cntr=.3,.1

Type RM Length L Ch R = 1 ,12215.95,44.14,42.57,94.55
BEGIN DESCRIPTION:
Survey Data Used for Points from Station 118.88 to 147.54.
.  All other Points obtained from LIDAR data.
END DESCRIPTION:
XS GIS Cut Line= 5
     3104210.963    13828387.566     3100472.069    13828263.876
     3100202.892    13828253.774     3100054.884    13828229.493
     3099038.233    13828182.112
#Sta/Elev= 30
       0   50.25  371.61   51.09  956.93   48.65 1734.97    48.7 2127.57   49.49
 2202.61   52.24 2481.73   50.26  3385.2   52.57 3521.87   52.34 3568.36   51.17
    3752   52.85 3843.23   52.52 3856.84   50.85 3871.46   50.52 3873.61   49.12
 3880.19   45.09 3880.45   43.07 3884.89   42.68 3889.93   42.96 3890.17   45.17
 3898.77   50.53 3899.19   50.79 3918.28   49.87 4157.53   53.28 4405.39   51.15
 4688.89   53.47 4890.72   53.36 4951.48   50.77 5011.54   52.69 5178.05   52.06
#Mann= 6 ,-1 , 0
       0      .1       0    3752      .1       0 3856.84     .08       0
 3873.61    .015       0 3898.77     .08       0 3918.28      .1       0
#XS Ineff= 4 ,-1
 -102.41 3787.95   52.87 3899.53 3979.29   50.83 4213.09 4683.51   53.32
 4694.51 5338.87   53.45
Permanent Ineff=
       F       F       F       F
Bank Sta=3871.46,3899.19
XS Rating Curve= 0
Exp/Cntr=.3,.1

Type RM Length L Ch R = 1 ,12173.38,511.24,511.42,516.88
XS GIS Cut Line= 4
     3103955.398     13828236.55     3100485.959    13828217.154
      3100290.18     13828215.98     3099040.797    13828161.597
#Sta/Elev= 30
       0    51.2  825.21   52.68  884.88   48.75  940.86   51.25 1045.86    51.6
 1327.77   50.06 1720.87    51.3 1825.25   49.08 1924.27   51.66 2227.39   49.85
 2284.61   51.73    3464   52.28 3551.39   52.59 3595.17   50.47 3604.14   45.09
 3604.51      43 3608.32   42.65 3613.97   43.15 3614.24   45.18 3623.56   50.74
 3624.54   50.53 3634.33   50.38  3670.9   52.52    3776    50.2 3918.53   53.29
 4136.35   51.38 4609.15   53.58 4691.87   50.81 4754.03   53.02 4915.84   52.84
#Mann= 6 ,-1 , 0
       0      .1       0    3464      .1       0 3581.47     .08       0
 3595.17    .015       0 3624.54     .08       0 3634.33      .1       0
#XS Ineff= 4 ,-1
  -81.78 3405.92   52.99 3670.91 3867.16   52.52 3953.99 4426.37   53.34
 4452.22 4999.28   53.67
Permanent Ineff=
       F       F       F       F
Bank Sta=3595.17,3623.56
XS Rating Curve= 0
Exp/Cntr=.3,.1

Type RM Length L Ch R = 1 ,11661.96,34.39,35.36,36.15
BEGIN DESCRIPTION:
Survey Data Used for Points from Station 114.94 to 143.32.
.  All other Points obtained from LIDAR data.
END DESCRIPTION:
XS GIS Cut Line= 4
      3103984.44    13827783.503     3100491.115    13827708.055
      3100227.41    13827702.583     3098651.166     13827664.07
#Sta/Elev= 30
       0   51.23  835.08   51.92  895.09   48.89  984.44   50.79 1120.14   49.18
 1195.16   50.79  1345.2   49.11  1780.3   50.57 1825.31   49.26 2258.25   49.26
 3237.63   52.56 3295.65   50.34    3490   52.31 3555.22      53 3604.74    50.3
 3605.28   50.31 3614.03   44.73  3614.2   42.62 3619.38   42.11 3623.87   42.63
 3624.12   44.73 3632.43   49.83 3632.92   50.14 3650.89   50.18 3720.26   52.76
 4300.92   53.77 4883.59   53.13 5037.39   51.01 5114.29      53 5334.62   52.49
#Mann= 5 ,-1 , 0
       0      .1       0    3490      .1       0 3604.74    .015       0
 3632.43     .08       0 3650.89      .1       0
#XS Ineff= 4 ,-1
  -119.6 3555.26      53 3828.27 4006.87   52.97 4038.39 4272.14   53.38
 4299.72 5423.86   53.77
Permanent Ineff=
       F       F       F       F
Bank Sta=3605.28,3632.92
XS Rating Curve= 0
Exp/Cntr=.5,.3

Type RM Length L Ch R = 1 ,11626.60,52.81,51.78,51.34
BEGIN DESCRIPTION:
Survey Data Used for Points from Station 116.39 to 145.11.
.  All other Points obtained from LIDAR data.
END DESCRIPTION:
XS GIS Cut Line= 4
     3103978.631    13827748.654     3100494.272    13827674.802
     3100221.307     13827664.91     3098682.658     13827625.58
#Sta/Elev= 30
       0   50.74  466.08   52.14  829.26   51.42  889.27   48.68 1042.28   51.34
 1114.32   49.18 1165.71   50.82 2443.91   49.23 2929.73   51.06 3298.65   50.05
 3428.27   50.61    3430   52.47 3580.54   51.95 3595.55   50.26 3614.04   50.07
 3614.63   49.68 3622.67   44.71 3623.34    42.6 3627.69   42.16 3632.71   42.59
 3632.91    44.7 3642.13   49.94 3822.83   53.08 3830.06   50.33 3853.44   50.27
 4580.31   53.21 4760.37   51.84  4865.4   53.15 5015.45   51.16 5297.44   52.11
#Mann= 6 ,-1 , 0
       0      .1       0    3430      .1       0 3595.55     .08       0
 3614.63    .015       0 3642.13     .08       0 3657.84      .1       0
#XS Ineff= 7 ,-1
 -348.21 3429.98   52.47 3443.33  3575.4   52.01 3606.87 3615.63   55.18
 3640.09 3650.13   55.18 3715.54 3781.04   51.75 3822.73 4530.64   53.08
  4865.4 5330.41   53.15
Permanent Ineff=
       F       F       F       F       F       F       F
Bank Sta=3614.04,3642.13
XS Rating Curve= 0
Exp/Cntr=.5,.3

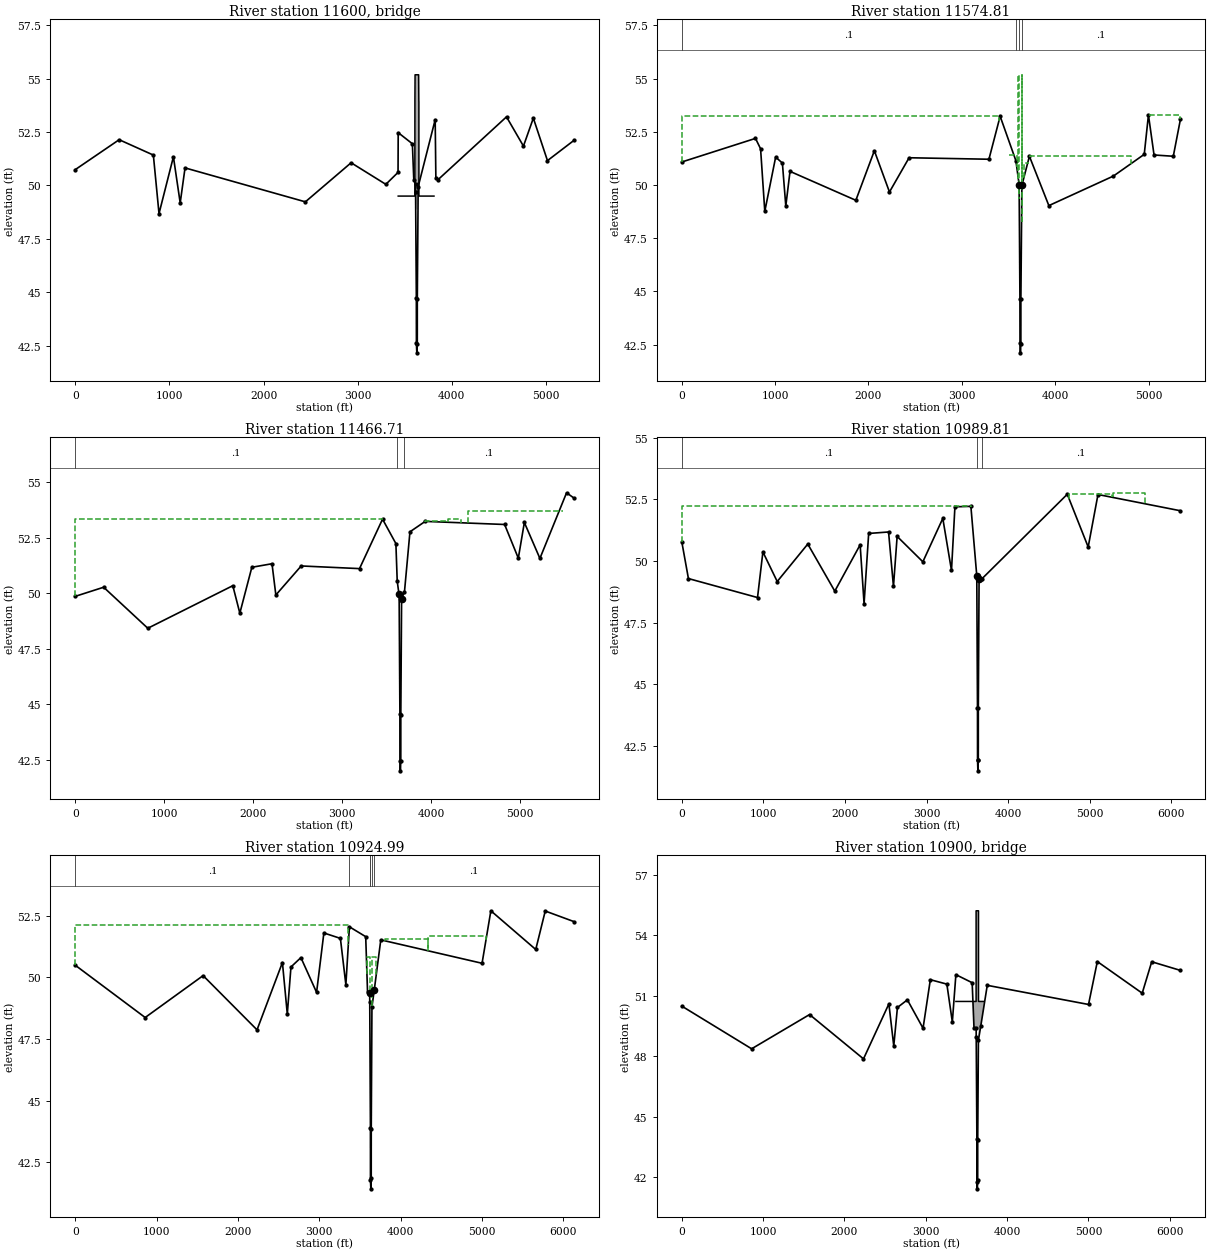
Type RM Length L Ch R = 3 ,11600   ,,,
BEGIN DESCRIPTION:
S3 Bridge
END DESCRIPTION:
Bridge Culvert--1,0,-1,-1, 0
Deck Dist Width WeirC Skew NumUp NumDn MinLoCord MaxHiCord MaxSubmerge Is_Ogee
1.1,44,2.6,0, 9, 9, , , .95, 0, 0,0,,
    3430 3606.64 3607.37 3609.05 3647.13 3649.04 3649.76    3650    3810
    49.5    49.5      54   55.18   55.18      54    53.9    49.5    49.5
      48   48.87   48.87   48.87   48.87   48.87   48.87   48.87      48
    3428 3604.64 3605.37 3607.05 3645.13 3647.04 3647.76    3648    3808
    49.5    49.5      54   55.18   55.18      54    53.9    49.5    49.5
      48   48.87   48.87   48.87   48.87   48.87   48.87   48.87      48
BR Coef=-1 , 1 , 0 ,1.25, 0 ,,,.8,0,2,0,
WSPro=,,,, 1 ,,,, 0 ,,,, 0 ,,,,-1 ,-1 ,-1 , 0 , 0 , 0 , 0 , 0
BC Design=,, 0 ,, 0 ,,,,,,
BC HTab HWMax=53.08

Type RM Length L Ch R = 1 ,11574.81,108.69,108.1,108.17
BEGIN DESCRIPTION:
Channel taken from surveyed cross-section 11626 and adjusted based on slope.  Overbanks obtained From LIDAR Data,
END DESCRIPTION:
XS GIS Cut Line= 5
     3103978.631    13827673.146      3100555.25     13827581.89
     3100504.556    13827621.133     3100225.622    13827615.453
     3098651.421    13827604.543
#Sta/Elev= 30
       0   51.08  789.84   52.19  844.37    51.7  889.39   48.76 1005.66   51.31
 1077.88   51.03 1114.47   49.01 1159.49   50.64 1864.74   49.28 2062.94   51.61
 2224.86   49.67 2434.94   51.28 3290.24   51.21 3410.29   53.23 3579.09   51.14
 3613.62   50.02 3622.26   44.66 3622.92   42.55 3627.27   42.11 3632.29   42.54
  3632.5   44.65  3643.2   49.98 3723.75   51.35 3932.04   49.03 4623.78   50.42
 4953.79   51.44 4998.79   53.29 5058.79   51.41 5265.04   51.35 5341.93    53.1
#Mann= 4 ,-1 , 0
       0      .1       0 3579.09     .08       0 3613.62    .015       0
  3643.2      .1       0
#XS Ineff= 7 ,-1
 -141.55 3395.83   53.23  3503.7 3588.74   51.39 3663.25 3715.28   51.04
 3725.21 4808.77   51.35 4999.46 5380.77   53.29 3604.93 3614.74   55.18
 3639.75 3647.75   55.18
Permanent Ineff=
       F       F       F       F       F       F       F
Bank Sta=3613.62,3643.2
XS Rating Curve= 0
Exp/Cntr=.5,.3

Type RM Length L Ch R = 1 ,11466.71,482.79,476.9,476.53
BEGIN DESCRIPTION:
Channel taken from surveyed cross-section 11626 and adjusted based on slope.  Overbanks obtained From LIDAR Data,
END DESCRIPTION:
XS GIS Cut Line= 4
     3104025.098    13827586.022     3100507.799    13827511.742
     3100228.921     13827508.73     3098415.892    13827492.726
#Sta/Elev= 30
       0   49.86  318.97   50.27  815.72   48.42 1771.96   50.34 1850.95    49.1
 1985.98   51.17 2212.75   51.33 2256.04   49.92 2541.11   51.23 3197.19   51.11
 3456.31   53.34 3606.33   52.24 3621.33   50.55 3640.94   49.96 3642.92    49.9
 3651.56   44.54 3652.22   42.43 3656.56   41.99 3661.58   42.42 3661.79   44.53
 3670.65   49.76 3702.65   50.05 3764.59   52.77 3936.35   53.24 4829.34    53.1
 4983.55   51.58 5051.46   53.19 5226.39   51.57 5526.41   54.53 5610.07   54.29
#Mann= 3 ,-1 , 0
       0      .1       0 3621.33    .015       0 3702.65      .1       0
#XS Ineff= 5 ,-1
 -139.02 3456.45   53.34 3811.96 3906.36   52.85 3934.13 4187.72   53.24
 4196.98 4333.95   53.35 4420.13 5488.21   53.72
Permanent Ineff=
       F       F       F       F       F
Bank Sta=3640.94,3670.65
XS Rating Curve= 0
Exp/Cntr=.3,.1

Type RM Length L Ch R = 1 ,10989.81,73.56,64.81,113.58
BEGIN DESCRIPTION:
Channel taken from surveyed cross-section 11626 and adjusted based on slope.  Overbanks obtained From LIDAR Data,
END DESCRIPTION:
XS GIS Cut Line= 4
     3104019.289    13827051.659     3100537.614    13827032.288
     3100241.268    13827035.299     3097909.149    13827021.669
#Sta/Elev= 30
    1.71   50.79   83.35   49.29  929.75   48.52  995.48   50.37 1171.03   49.17
 1545.24   50.69 1876.12   48.78 2186.68   50.66 2234.77   48.27  2291.1   51.12
 2534.77   51.18 2594.77   48.97 2639.77      51 2954.78   49.97 3199.14   51.73
 3305.47   49.62 3347.51    52.2 3543.01   52.22 3615.28    49.4 3623.91   44.04
 3624.57   41.93 3628.92   41.49 3633.93   41.92 3634.14   44.03 3643.44   49.27
 3678.15   49.28 4723.72   52.71 4979.82   50.57 5099.82    52.7 6110.25   52.04
#Mann= 3 ,-1 , 0
    1.71      .1       0 3615.28    .015       0 3678.15      .1       0
#XS Ineff= 3 ,-1
       0  3543.9   52.22 4744.37 5271.73   52.71 5278.79 5677.41   52.77
Permanent Ineff=
       F       F       F
Bank Sta=3615.28,3643.44
XS Rating Curve= 0
Exp/Cntr=.5,.3

Type RM Length L Ch R = 1 ,10924.99,62.93,53.49,53.26
XS GIS Cut Line= 5
     3104030.906    13827022.617     3100646.852    13827011.718
     3100557.457    13826969.893       3100271.6    13826968.431
     3097909.149    13826957.434
#Sta/Elev= 30
       0   50.49  859.08   48.37 1571.36   50.07  2234.2   47.87 2546.36    50.6
 2606.36   48.51 2651.36   50.42 2773.57    50.8 2966.36   49.39 3055.98    51.8
  3259.1   51.58 3326.37    49.7    3370   52.05 3570.25   51.65 3592.54   49.42
  3619.1   49.38 3619.96   48.98 3628.23   43.88 3628.62   41.78 3633.41   41.42
 3638.11   41.85  3638.4   43.84 3646.88    48.8 3675.25   49.48 3755.67   51.52
 5000.68   50.57 5108.89    52.7 5660.69   51.13 5777.44   52.69  6131.1   52.26
#Mann= 6 ,-1 , 0
       0      .1       0    3370      .1       0  3619.1     .08       0
 3619.96    .015       0 3646.88     .08       0 3675.25      .1       0
#XS Ineff= 5 ,-1
 -176.79  3356.3   52.13 3585.39  3618.6   50.81 3648.18 3696.02   50.81
 3801.84 4330.06   51.56 4340.93    5048   51.69
Permanent Ineff=
       F       F       F       F       F
Bank Sta=3619.1,3675.25
XS Rating Curve= 0
Exp/Cntr=.5,.3

Type RM Length L Ch R = 3 ,10900   ,,,
BEGIN DESCRIPTION:
S4 Walkway
END DESCRIPTION:
Bridge Culvert--1,0,-1,-1, 0
Deck Dist Width WeirC Skew NumUp NumDn MinLoCord MaxHiCord MaxSubmerge Is_Ogee
21,9.95,2.6,0, 6, 6, , , .95, 0, 0,0,,
    3370 3618.58 3618.59 3648.18 3648.19    3718
   50.72   50.72   55.22   55.22   50.72   50.72
      46      46   49.37   49.37      46      46
    2865 3132.78 3132.78 3162.57 3162.57    3308
   50.72   50.72   55.22   55.22   50.72   50.72
      42      42   49.37   49.37      42      42
BR Coef=-1 , 1 , 0 ,1.25, 0 ,,,.8,-1,2,0,
WSPro=,,,, 1 ,,,, 0 ,,,, 0 ,,,,-1 ,-1 ,-1 , 0 , 0 , 0 , 0 , 0
BC Design=,, 0 ,, 0 ,,,,,,
BC HTab HWMax=52.05

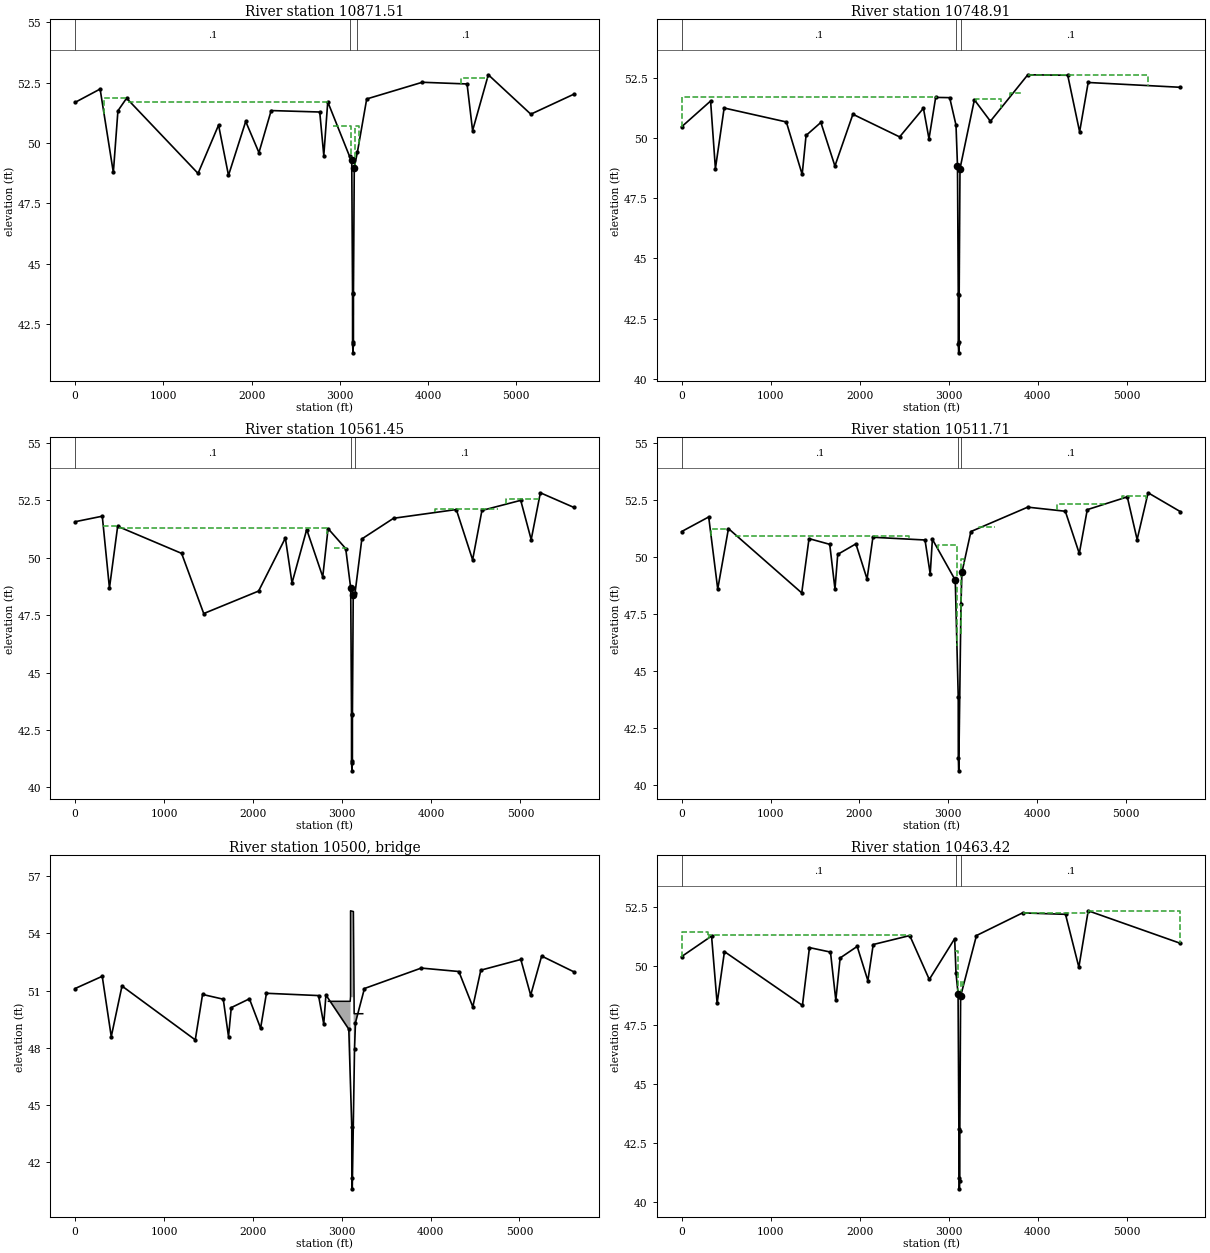
Type RM Length L Ch R = 1 ,10871.51,133.14,122.6,124.23
BEGIN DESCRIPTION:
Channel survey copied from surveyed section 10924 and adjusted based on channel slope. Overbanks from LIDAR
END DESCRIPTION:
XS GIS Cut Line= 5
     3103537.201     13826912.26     3100667.814    13826877.324
     3100559.912     13826915.07     3100266.286    13826916.026
     3097890.117    13826924.127
#Sta/Elev= 30
       0   51.68  282.66   52.23  432.68   48.78  484.57   51.33  582.69   51.85
 1392.75   48.74 1625.21   50.74 1737.77   48.66 1932.79   50.89  2082.8    49.6
 2221.49   51.34 2771.92   51.28 2817.85   49.48 2862.68    51.7 3109.55   49.45
 3134.65   49.28 3143.77   43.78 3144.16   41.68 3148.95   41.32 3153.65   41.75
 3153.94   43.74 3163.19   48.98 3199.27   49.63 3304.27   51.82 3934.27   52.51
 4441.69   52.44 4504.28   50.51 4682.52   52.82 5164.22   51.19 5653.73   52.02
#Mann= 3 ,-1 , 0
       0      .1       0 3109.55    .015       0 3199.27      .1       0
#XS Ineff= 6 ,-1
  326.84  583.19   51.85  594.42 2862.85    51.7 2922.91    3128   50.72
 3167.65 3212.79   50.72 3314.16 3723.51   51.81 4369.17 4670.26   52.69
Permanent Ineff=
       F       F       F       F       F       F
Bank Sta=3134.65,3163.19
XS Rating Curve= 0
Exp/Cntr=.5,.3

Type RM Length L Ch R = 1 ,10748.91,214.15,187.46,186.84
BEGIN DESCRIPTION:
Channel survey copied from surveyed section 10924 and adjusted based on channel slope. Overbanks from LIDAR
END DESCRIPTION:
XS GIS Cut Line= 4
     3103513.968    13826813.519     3100563.514    13826796.175
     3100238.859    13826790.151     3097909.149    13826745.697
#Sta/Elev= 30
       0   50.47  325.39   51.54  379.42   48.73  477.55   51.25 1176.44   50.67
 1354.43   48.49 1398.08   50.11 1564.44   50.65 1722.35   48.84 1924.44   50.99
 2449.45   50.05 2716.94   51.24 2779.46   49.97 2854.46   51.69 3011.93   51.68
 3082.94   50.54 3099.76   48.84 3108.33   43.54 3108.71   41.44 3113.51   41.08
  3118.2   41.51  3118.5    43.5 3127.79   48.73 3289.52   51.59 3469.55    50.7
 3889.63   52.63 4338.36   52.61  4472.1   50.26  4568.3   52.31 5605.35   52.11
#Mann= 3 ,-1 , 0
       0      .1       0 3082.94    .015       0    3139      .1       0
#XS Ineff= 4 ,-1
  -72.03 2854.24   51.69 3303.07 3586.88   51.64 3693.89 3825.72   51.89
 3889.56 5241.92   52.63
Permanent Ineff=
       F       F       F       F
Bank Sta=3099.76,3127.79
XS Rating Curve= 0
Exp/Cntr=.3,.1

Type RM Length L Ch R = 1 ,10561.45,52.85,49.75,51.46
BEGIN DESCRIPTION:
Channel survey copied from surveyed section 10924 and adjusted based on channel slope. Overbanks from LIDAR
END DESCRIPTION:
XS GIS Cut Line= 5
     3103513.968    13826679.928     3100674.893    13826628.488
     3100577.669    13826605.236     3100253.014    13826606.441
     3097916.286    13826636.259
#Sta/Elev= 30
       0   51.57  304.46   51.81  384.85   48.68  477.08   51.37  1195.3   50.19
 1443.45   47.57 2059.75   48.55 2360.21   50.86 2434.81    48.9 2599.84   51.23
 2779.87   49.17 2839.54   51.27 3037.62    50.4 3093.78   48.68 3102.91   43.18
 3103.29   41.08 3108.09   40.72 3112.79   41.15 3113.08   43.14 3121.99   48.37
 3142.62   48.47 3218.93   50.82 3574.82   51.72 4279.52    52.1 4462.72   49.91
 4567.24   52.06 5002.76    52.5 5120.28   50.79 5223.35   52.83 5601.08   52.19
#Mann= 3 ,-1 , 0
       0      .1       0 3093.78    .015       0 3142.62      .1       0
#XS Ineff= 5 ,-1
  313.27  476.56   51.37  495.15 2833.14   51.29 2905.48 3037.47   50.41
 4041.28  4747.6   52.14 4837.79 5210.32   52.55
Permanent Ineff=
       T       F       F       F       F
Bank Sta=3093.78,3121.99
XS Rating Curve= 0
Exp/Cntr=.5,.3

Type RM Length L Ch R = 1 ,10511.71,55.33,48.28,47.53
BEGIN DESCRIPTION:
Survey Data Used for Points from Station 155.69 to 176.23.
.  All other Points obtained from LIDAR data.
END DESCRIPTION:
XS GIS Cut Line= 6
     3103525.585     13826604.42     3100676.762    13826536.887
     3100581.187    13826558.306     3100252.245    13826554.215
     3100207.539    13826555.581     3097916.286    13826624.364
#Sta/Elev= 30
       0   51.11  304.57   51.75  406.14   48.59  526.82   51.24 1351.41   48.42
 1433.57    50.8  1666.5   50.55 1725.57   48.59 1756.52   50.11 1960.84   50.57
 2086.61   49.03 2152.46   50.86 2738.73   50.74 2797.36   49.25 2821.82   50.77
 3079.21   48.98 3112.66   43.86 3113.52   41.19 3118.32   40.62 3143.59   47.93
 3154.21   49.32 3255.17   51.11 3894.61   52.18 4317.59      52 4474.76   50.15
 4564.81   52.07 5015.01   52.63 5125.77   50.76 5249.26   52.81 5613.55   51.98
#Mann= 3 ,-1 , 0
       0      .1       0 3112.66    .015       0 3143.59      .1       0
#XS Ineff= 7 ,-1
  331.71  526.86   51.24  599.35 2553.76   50.91 2882.19    3098   50.54
    3139    3174   49.91 3344.86  3528.4   51.33 4222.52 4772.47   52.32
 4954.83 5229.81   52.67
Permanent Ineff=
       F       F       F       F       F       F       F
Bank Sta=3079.21,3154.21
XS Rating Curve= 0
Exp/Cntr=.5,.3

Type RM Length L Ch R = 3 ,10500   ,,,
Bridge Culvert--1,0,-1,-1, 0
Deck Dist Width WeirC Skew NumUp NumDn MinLoCord MaxHiCord MaxSubmerge Is_Ogee
19.14,10,2.6,0, 8, 9, , , .95, 0, 0,0,,
    2850 3094.83 3098.74 3098.75 3131.31 3138.93 3139.64    3236
   50.44   50.44   50.68   55.18   55.14   50.45   49.79   49.79
      44      44      44   50.68   50.64      44      44      44
    2854 3098.83 3102.74 3102.75 3135.31 3142.93 3143.64 3149.52    3189
   50.54   50.54   50.68   55.18   55.14   50.45   49.79   49.41   49.41
      44      44      44   50.68   50.64      44      44      44      44
BR Coef=-1 , 1 , 0 ,1.25, 0 ,,,.8,0,2,0,
WSPro=,,,, 1 ,,,, 0 ,,,, 0 ,,,,-1 ,-1 ,-1 , 0 , 0 , 0 , 0 , 0
BC Design=,, 0 ,, 0 ,,,,,,
BC HTab HWMax=51.14

Type RM Length L Ch R = 1 ,10463.42,118.51,95.19,204.98
BEGIN DESCRIPTION:
Channel survey taken from stations 252.43 - 281.11
END DESCRIPTION:
XS GIS Cut Line= 6
     3103531.393    13826552.146     3100678.799    13826507.515
      3100584.46    13826508.392     3100247.335    13826507.574
     3100201.931    13826506.976     3097928.182    13826474.482
#Sta/Elev= 30
       0    50.4  336.18   51.27  398.56   48.42  480.98   50.61    1357   48.33
 1436.05   50.78 1672.04   50.59 1732.05   48.55 1780.41   50.34 1972.08   50.83
 2092.09   49.38  2152.1   50.91 2562.68   51.29 2782.18   49.43 3067.19   51.16
 3082.09    49.7 3105.38   48.83 3114.54   43.08 3114.97   41.02 3119.62   40.56
 3124.64   40.91 3124.93      43 3134.05   48.72 3138.13   48.78 3311.82   51.29
  3829.5   52.25  4312.3   52.19 4462.31   49.95 4567.32   52.34  5603.8   50.96
#Mann= 3 ,-1 , 0
       0      .1       0 3082.09    .015       0 3138.13      .1       0
#XS Ineff= 6 ,-1
  -23.48  292.08   51.44  311.23 2563.22    51.3    3070    3102   50.64
 3137.46    3165   49.35 3830.94 4561.16   52.26 4567.23 5683.07   52.34
Permanent Ineff=
       F       F       F       F       F       F
Bank Sta=3105.38,3134.05
XS Rating Curve= 0
Exp/Cntr=.5,.3

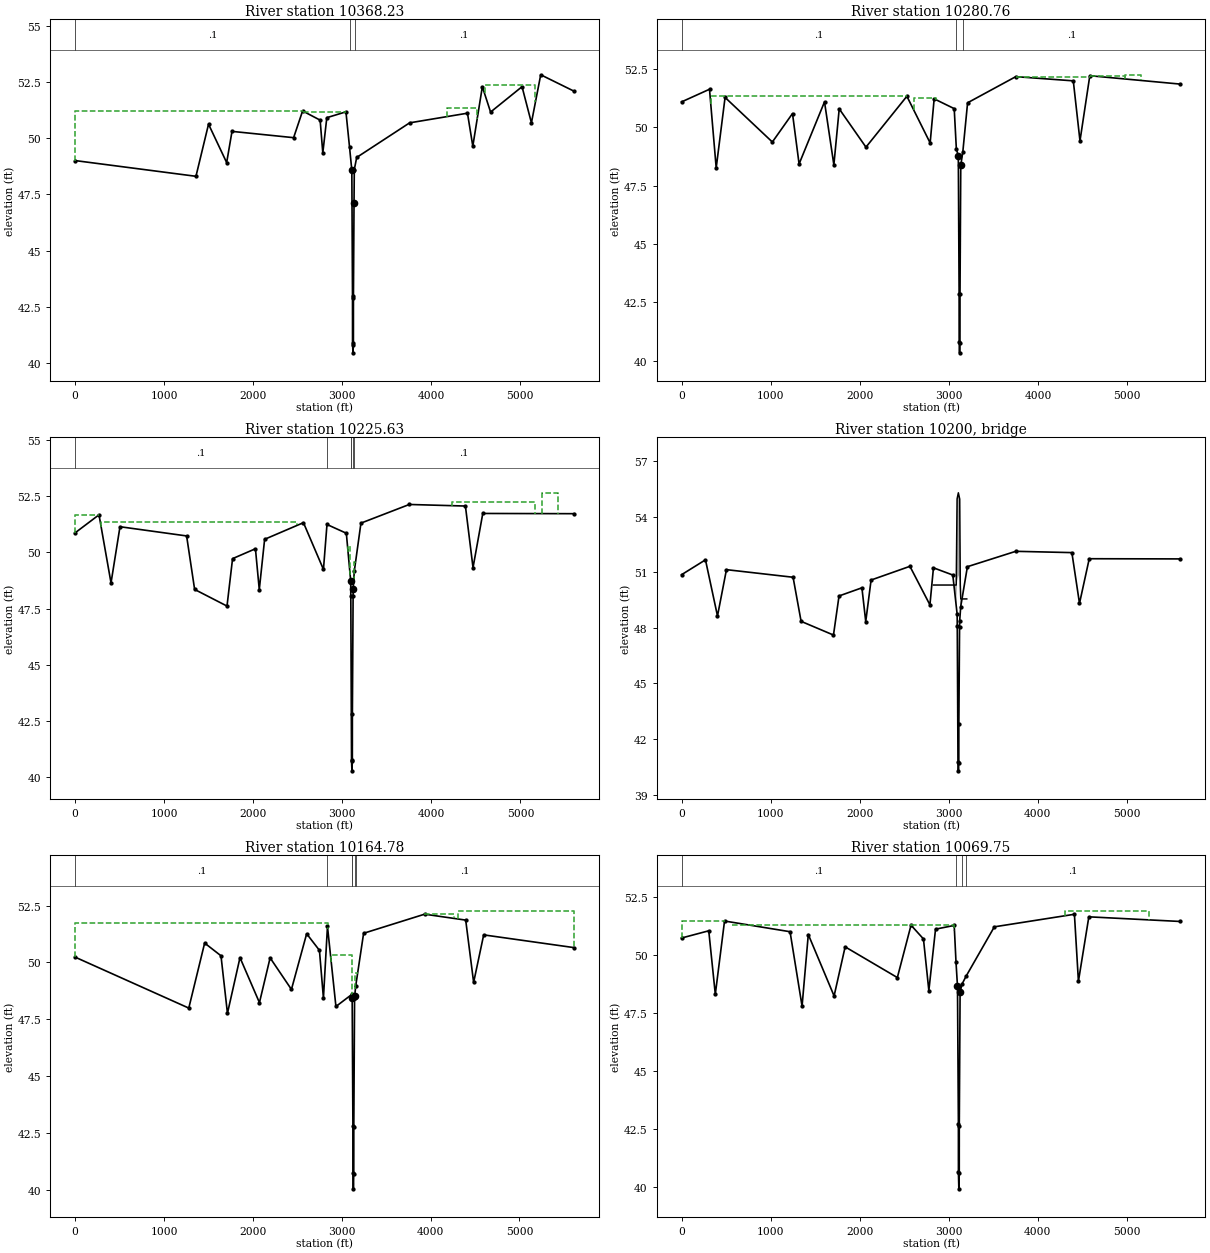
Type RM Length L Ch R = 1 ,10368.23,115.48,87.47,185.36
BEGIN DESCRIPTION:
Channel copied from surveyed section 10463. Overbanks from LIDAR
END DESCRIPTION:
XS GIS Cut Line= 6
     3103531.393    13826494.063     3100646.852    13826435.938
     3100584.897    13826410.684      3100553.82    13826411.083
     3100256.628      13826414.9      3097932.94    13826353.149
#Sta/Elev= 30
       0   49.01 1357.11   48.31 1498.43   50.63 1702.18   48.92 1762.19   50.31
 2454.37   50.03 2555.37   51.22 2752.39   50.81  2782.4   49.35 2827.41   50.92
 3042.38   51.18 3082.66   49.61 3108.39   48.58 3116.07   42.97  3116.5   40.91
 3121.15   40.45 3126.17    40.8 3126.46   42.89  3133.1   47.12 3136.27   48.61
  3163.2   49.15 3757.94   50.69  4407.8   51.12 4467.82   49.65 4574.93    52.3
 4667.42   51.17 5020.85    52.3 5126.33   50.69 5230.84   52.83 5604.83    52.1
#Mann= 3 ,-1 , 0
       0      .1       0 3082.66    .015       0 3138.71      .1       0
#XS Ineff= 4 ,-1
  -53.37 2555.32   51.22 2559.02  3042.3   51.18 4177.64 4517.46   51.36
 4599.73 5172.05   52.36
Permanent Ineff=
       F       F       F       F
Bank Sta=3108.39,3133.1
XS Rating Curve= 0
Exp/Cntr=.3,.1

Type RM Length L Ch R = 1 ,10280.76,55.91,55.13,57.63
BEGIN DESCRIPTION:
Channel copied from surveyed section 10225
END DESCRIPTION:
XS GIS Cut Line= 6
     3103537.201    13826372.089     3100678.451    13826329.543
      3100580.38    13826328.165     3100261.747    13826322.744
     3100163.909    13826312.258     3097942.456    13826257.986
#Sta/Elev= 30
       0   51.09  312.61   51.63  387.69   48.26  487.21   51.28 1017.76   49.37
 1243.78   50.59 1317.59   48.43 1602.82   51.09 1707.83   48.39 1767.84   50.79
 2067.87   49.15 2526.97   51.33 2787.95   49.33 2832.96   51.22 3057.98    50.8
 3082.22   49.06 3104.01   48.79 3112.94   42.86 3113.44    40.8 3117.91   40.34
 3122.53   40.78 3122.92   42.85 3131.45   48.37 3154.39   48.94 3208.01   51.05
 3748.69   52.17 4393.88   51.99  4468.9   49.42 4579.18   52.21 5596.34   51.85
#Mann= 3 ,-1 , 0
       0      .1       0 3082.22    .015       0 3154.39      .1       0
#XS Ineff= 6 ,-1
  326.78 2526.72   51.33 2606.25 2857.32   51.26 3447.71 3724.99   51.35
 3747.81 4577.78   52.17 4579.18 4977.51   52.21 4979.06  5154.8   52.25
Permanent Ineff=
       F       F       F       F       F       F
Bank Sta=3104.01,3131.45
XS Rating Curve= 0
Exp/Cntr=.5,.3

Type RM Length L Ch R = 1 ,10225.63,60.33,60.85,61.41
BEGIN DESCRIPTION:
Survey Data Used for Points from Station 266.3 to 293.76.  All other Points obtained from LIDAR data.
END DESCRIPTION:
XS GIS Cut Line= 5
     3103537.201    13826302.389     3100697.326    13826306.949
     3100575.099    13826271.856     3100270.844    13826268.834
     3097940.077    13826238.954
#Sta/Elev= 30
       0   50.87  267.64   51.67  402.64   48.64  503.26   51.14 1251.59   50.73
 1341.57   48.35 1705.19   47.61 1767.65   49.72 2024.59   50.16 2067.65   48.34
 2127.65   50.58 2563.72   51.32 2788.36   49.24    2828   51.24 3045.37   50.85
  3094.3   48.73 3095.49   48.08 3103.73   40.74  3108.2   40.28 3112.81   40.72
  3113.2   42.79 3121.38   48.06 3122.67   48.38 3134.32   49.15 3209.37    51.3
 3752.64   52.13 4382.69   52.06 4468.15   49.32 4577.71   51.73 5602.27   51.72
#Mann= 6 ,-1 , 0
       0      .1       0    2828      .1       0  3094.3     .08       0
 3095.49    .015       0 3121.38     .08       0 3134.32      .1       0
#XS Ineff= 6 ,-1
  -35.89  264.75   51.66  291.12 2495.83   51.35 3064.21    3088   50.29
    3127 3147.41   49.57 4230.77    5168   52.25 5237.64 5426.25   52.65
Permanent Ineff=
       F       F       F       F       F       F
Bank Sta=3094.3,3122.67
XS Rating Curve= 0
Exp/Cntr=.5,.3

Type RM Length L Ch R = 3 ,10200   ,,,
BEGIN DESCRIPTION:
S6 Walkway
END DESCRIPTION:
Bridge Culvert--1,0,-1,-1, 0
Deck Dist Width WeirC Skew NumUp NumDn MinLoCord MaxHiCord MaxSubmerge Is_Ogee
25,10,2.6,0, 8, 9, , , .95, 0, 0,0,,
    2828 3083.78 3093.48 3107.78 3123.04 3129.52 3135.03    3202
   50.31   50.31   54.96   55.29   54.95   50.31   49.56   49.56
      44      44   50.51   50.84    50.5      44      44      44
    2834    2978 3109.78 3119.48 3133.78 3149.04 3155.52 3161.03    3228
   50.31   50.31   50.31   54.96   55.29   54.95   50.31   49.56   49.56
      44      44      44   50.51   50.84    50.5      44      44      44
BR Coef=-1 , 1 , 0 ,1.25, 0 ,,,.8,-1,2,0,
WSPro=,,,, 1 ,,,, 0 ,,,, 0 ,,,,-1 ,-1 ,-1 , 0 , 0 , 0 , 0 , 0
BC Design=,, 0 ,, 0 ,,,,,,
BC HTab HWMax=51.33

Type RM Length L Ch R = 1 ,10164.78,95.57,95.03,94.47
BEGIN DESCRIPTION:
Survey Data Used for Points from Station 282.65 to 310.92.  All other Points obtained from LIDAR data.
END DESCRIPTION:
XS GIS Cut Line= 5
      3103543.01    13826215.265     3100710.361    13826159.358
      3100579.98    13826211.888     3100270.611    13826207.239
     3097940.077    13826167.581
#Sta/Elev= 30
       0   50.23  1278.7   47.99 1457.13   50.85 1641.12   50.29 1713.79   47.76
  1854.9   50.21 2073.86   48.23 2193.88    50.2 2433.93   48.81 2605.23   51.26
 2748.99   50.53    2794   48.43 2839.43   51.58 2934.65   48.06 3116.58    48.6
 3117.48   48.43  3125.8   42.81 3126.15   40.75 3130.97   40.04 3135.46    40.7
 3135.82   42.76 3144.48   48.42 3144.92    48.5 3157.98   48.98 3246.16   51.28
 3932.51   52.12 4395.12   51.86  4484.4   49.12 4597.53   51.21 5614.04   50.65
#Mann= 6 ,-1 , 0
       0      .1       0 2839.43      .1       0 3116.58     .08       0
 3117.48    .015       0 3144.48     .08       0 3157.98      .1       0
#XS Ineff= 5 ,-1
  -41.71 2842.11   51.73    2882  3110.5   50.31    3154 3178.42   49.55
 3928.55 4258.54   52.11 4309.56 5656.73   52.27
Permanent Ineff=
       F       F       F       F       F
Bank Sta=3117.48,3144.92
XS Rating Curve= 0
Exp/Cntr=.5,.3

Type RM Length L Ch R = 1 ,10069.75,557.79,557.82,558.35
BEGIN DESCRIPTION:
Channel copied from surveyed section 10164. Overbanks from LIDAR
END DESCRIPTION:
XS GIS Cut Line= 6
      3103543.01    13826128.141     3100695.735    13826116.812
      3100588.21    13826116.145     3100272.589    13826113.133
      3100034.91    13826134.379     3097937.698    13826115.242
#Sta/Elev= 30
       0   50.72  304.76   51.03  378.46    48.3   482.1   51.45 1218.46   50.99
 1353.46   47.79 1423.52   50.87 1713.47   48.23 1837.59   50.34 2424.39   49.02
 2578.17   51.27 2717.71   50.68 2778.47   48.46 2853.47    51.1 3063.48   51.26
 3083.51   49.69 3100.33   48.64 3110.41   42.71 3110.76   40.65 3115.58   39.94
 3120.07    40.6 3120.43   42.66 3129.53    48.4 3152.65   48.75 3197.24   49.08
 3514.44    51.2 4414.48   51.74 4459.48   48.86 4576.54   51.63 5606.38   51.43
#Mann= 4 ,-1 , 0
       0      .1       0 3083.51    .015       0 3152.65     .09       0
 3197.24      .1       0
#XS Ineff= 5 ,-1
  -25.28  482.44   51.45  486.29  558.33   51.35     565 2577.63   51.27
 2579.18  3066.4   51.26 4309.12 5247.56   51.89
Permanent Ineff=
       F       F       F       F       F
Bank Sta=3100.33,3129.53
XS Rating Curve= 0
Exp/Cntr=.3,.1