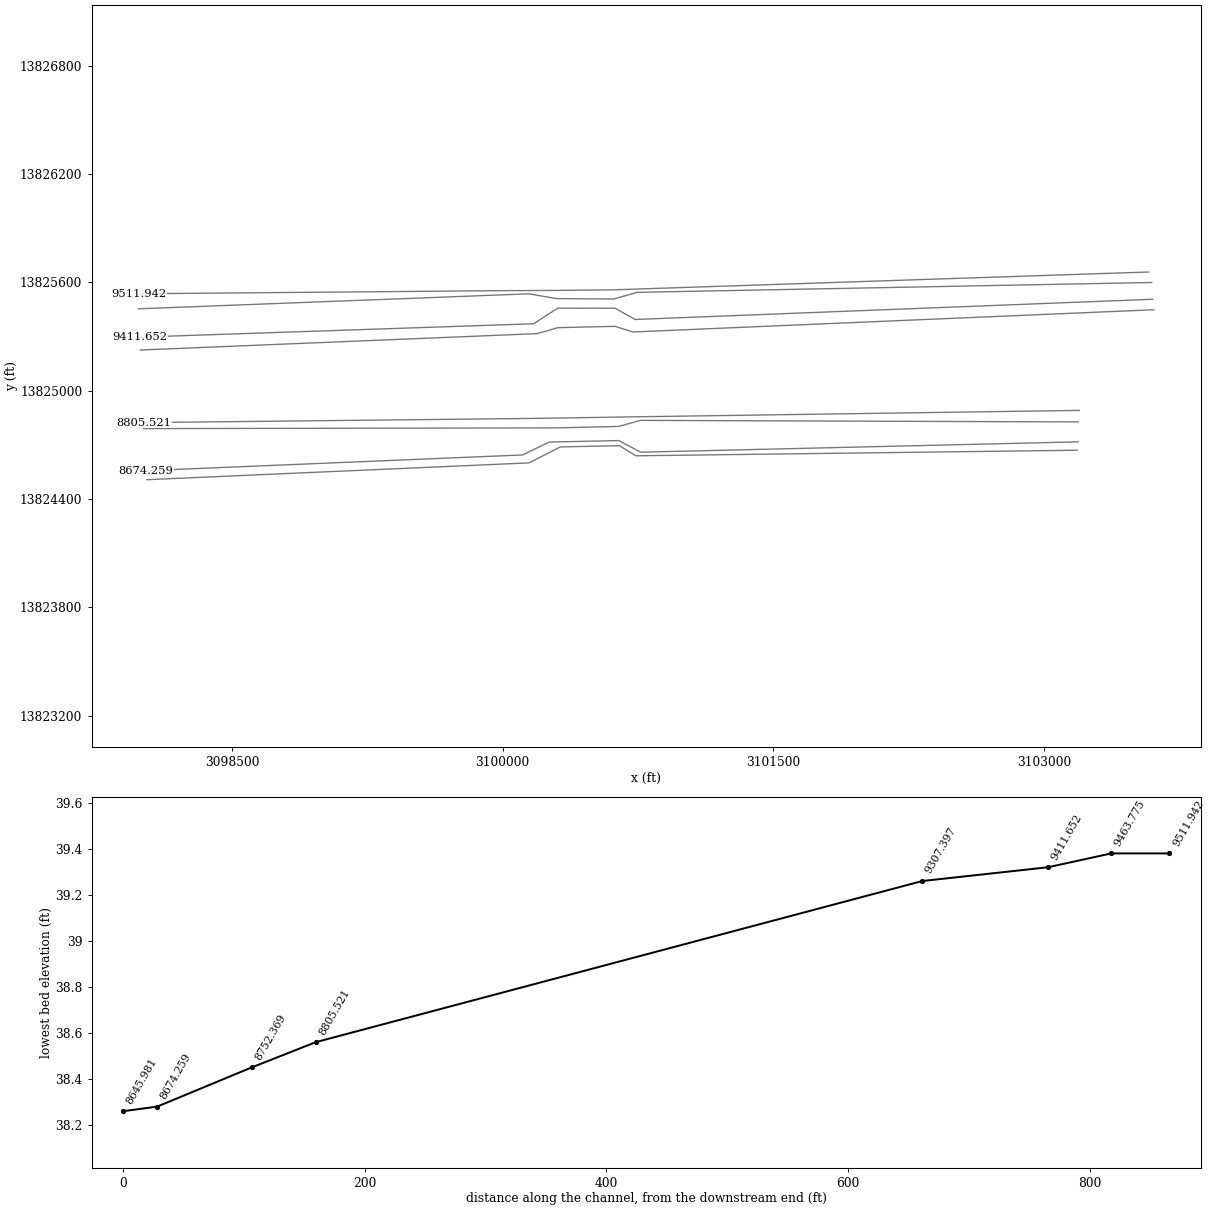
HEC-RAS study D111-00-00.prj: D111-00-00

--- D111-00-00.g01 (geometry) --- (continued)

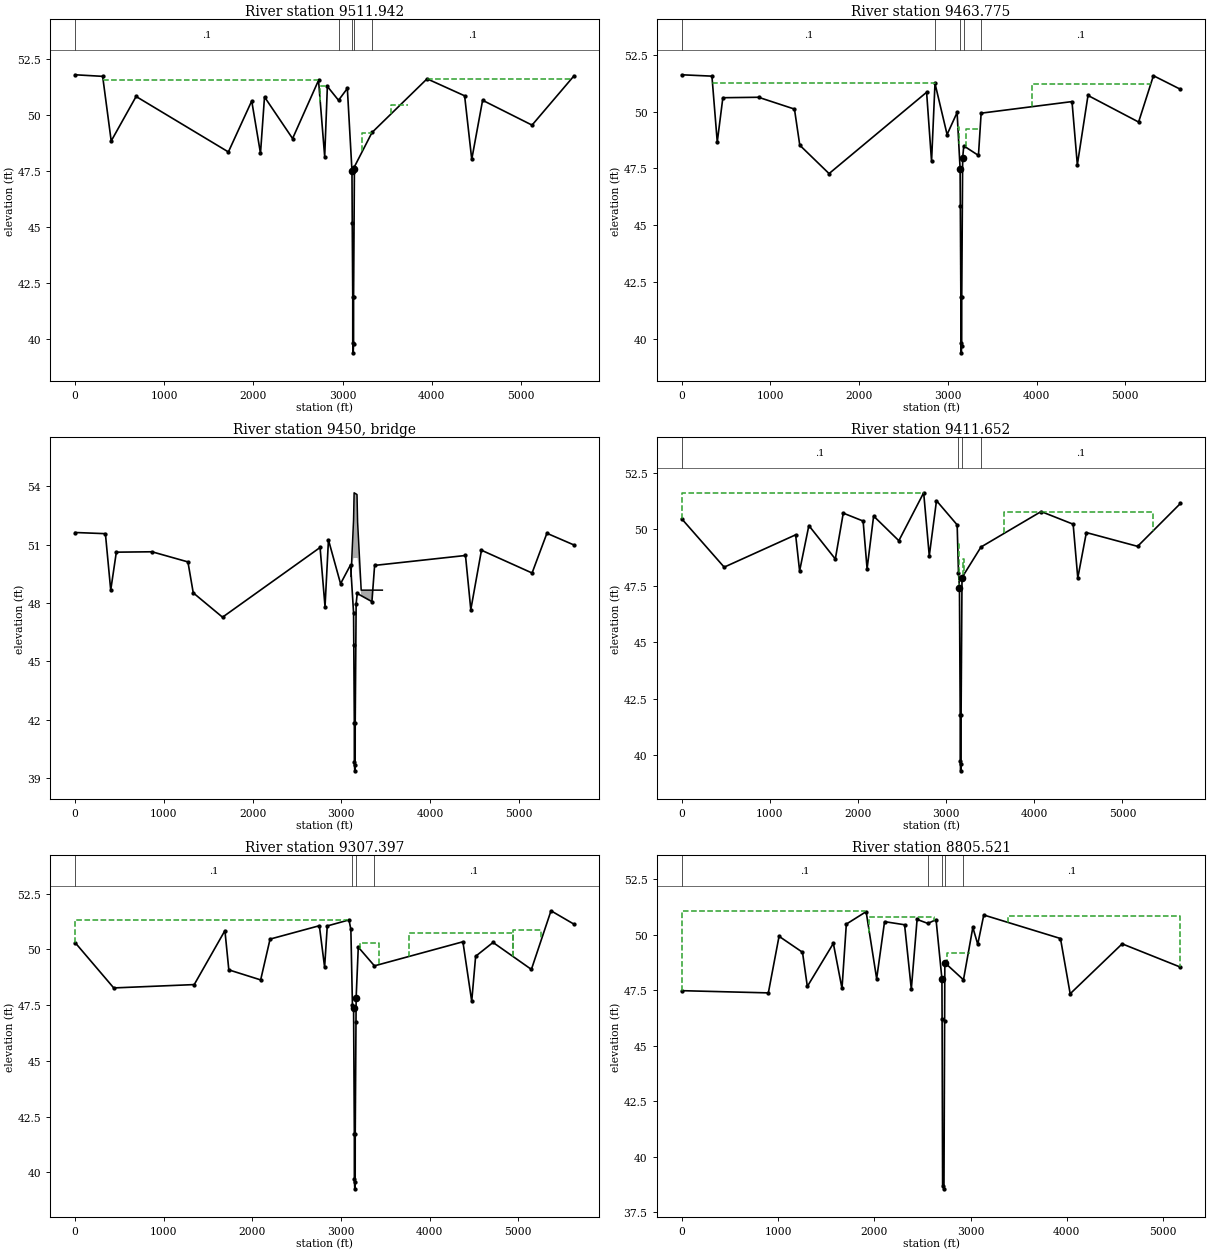
Type RM Length L Ch R = 1 ,9511.942,69.97,48.17,50.69
XS GIS Cut Line= 5
     3103577.859    13825657.669     3100614.962    13825558.982
     3100300.944    13825555.728     3099999.042    13825554.406
     3097982.901    13825537.126
#Sta/Elev= 30
       0   51.81  308.47   51.74  404.34   48.85  683.68   50.84 1719.25   48.36
 1981.12   50.64 2079.45    48.3 2124.48   50.82 2439.65   48.96 2730.63   51.56
 2799.85   48.15 2829.87   51.29    2955   50.67 3054.06    51.2 3105.91   47.52
 3108.98    45.2 3114.64   41.89 3114.68   39.84 3119.48   39.38 3123.88   39.78
 3124.07   41.86 3133.33    47.6 3133.62    47.7 3330.72   49.23 3948.65   51.63
 4369.94   50.87    4450   48.03 4571.67   50.67 5126.45   49.56 5596.69   51.76
#Mann= 5 ,-1 , 0
       0      .1       0    2955      .1       0 3108.98    .015       0
 3133.62     .09       0 3330.72      .1       0
#XS Ineff= 5 ,-1
  314.34 2730.23   51.56 2750.46 2830.05   51.29 3223.06 3331.87   49.21
 3547.03 3740.21   50.45 3948.68 5559.27   51.63
Permanent Ineff=
       F       F       F       F       F
Bank Sta=3105.91,3133.33
XS Rating Curve= 0
Exp/Cntr=.5,.3

Type RM Length L Ch R = 1 ,9463.775,51.91,52.12,59.38
BEGIN DESCRIPTION:
Channel taken from survey for stations 283.02 - 311.92
END DESCRIPTION:
XS GIS Cut Line= 6
     3103595.284    13825599.586     3100744.929    13825545.099
     3100613.799    13825507.847     3100298.387    13825510.403
     3100144.914     13825536.75     3097982.901    13825453.859
#Sta/Elev= 30
       0   51.62  340.79   51.56   400.8   48.66  463.95   50.61  865.89   50.63
 1270.96   50.11 1330.97   48.52 1661.03   47.27 2760.48   50.85 2816.24   47.81
    2855   51.24 2991.32   48.99 3104.22   49.96 3138.02   47.49 3140.51   45.84
 3146.53   41.83 3146.67   39.82  3151.5   39.38 3155.94   39.68 3156.51   41.84
 3166.92   47.96 3179.22   48.49 3344.77   48.07 3375.21   49.93 4399.38   50.44
 4459.43   47.66 4579.51   50.71 5149.94   49.54  5317.1   51.58 5621.94   50.98
#Mann= 5 ,-1 , 0
       0      .1       0    2855      .1       0 3140.51    .015       0
 3179.22     .09       0 3375.21      .1       0
#XS Ineff= 4 ,-1
  346.53 2855.74   51.24  3108.2    3123   49.33  3198.9    3367   49.24
  3951.7 5289.76   51.21
Permanent Ineff=
       F       F       F       F
Bank Sta=3138.02,3166.92
XS Rating Curve= 0
Exp/Cntr=.5,.3

Type RM Length L Ch R = 3 ,9450    ,,,
BEGIN DESCRIPTION:
S7 Road Crossing
END DESCRIPTION:
Bridge Culvert--1,0,-1,-1, 0
Deck Dist Width WeirC Skew NumUp NumDn MinLoCord MaxHiCord MaxSubmerge Is_Ogee
3.5,45.2,2.6,0, 7, 8, , , .95, 0, 0,0,,
 3108.53 3137.95 3144.09 3176.76 3183.39 3224.16 3462.46
   49.37   52.27   53.66   53.57   52.16   48.66   48.66
      46   50.31   50.31   50.31   50.31      46      46
    2875    3145 3156.83 3165.11 3173.51 3182.73 3195.31 3479.79
   49.37   49.37   52.27   53.66   53.57   52.16   48.66   48.66
      46      46   50.31   50.31   50.31   50.31      46      46
BR Coef=-1 , 1 , 0 ,1.25, 0 ,,,.8,0,2,0,
WSPro=,,,, 1 ,,,, 0 ,,,, 0 ,,,,-1 ,-1 ,-1 , 0 , 0 , 0 , 0 , 0
BC Design=,, 0 ,, 0 ,,,,,,
BC HTab HWMax=51.24

Type RM Length L Ch R = 1 ,9411.652,105.14,104.25,131.69
BEGIN DESCRIPTION:
Cross Section Obtained From LIDAR Data, With Channel survey copied from 9463 and interpolated Based on Slope
END DESCRIPTION:
XS GIS Cut Line= 6
     3103601.092    13825506.654      3100733.78    13825394.674
     3100622.051    13825457.176     3100304.314    13825456.944
     3100170.557    13825370.925     3097987.659     13825296.84
#Sta/Elev= 30
       0   50.47   481.9   48.33 1292.52   49.76 1337.55   48.16 1442.63   50.17
 1742.86   48.69 1832.93   50.72  2058.1   50.37 2103.14   48.26  2177.3   50.59
 2463.41    49.5 2745.15   51.62 2808.67   48.83 2890.51   51.27 3125.01    50.2
 3140.01   48.08 3151.05   47.43 3159.56   41.77  3159.7   39.76 3164.53   39.32
 3168.97   39.62 3169.54   41.78 3180.04   47.87 3395.06   49.22 4077.76   50.79
 4440.84   50.23 4493.42   47.85 4590.69   49.86 5172.02   49.25 5658.44   51.15
#Mann= 4 ,-1 , 0
       0      .1       0 3140.01    .015       0 3180.04     .09       0
 3395.06      .1       0
#XS Ineff= 5 ,-1
 -213.92 2745.33   51.62    3130 3148.86   49.36 3191.22 3204.81   48.68
 3660.42 4074.76   50.77 4077.85 5345.92   50.79
Permanent Ineff=
       F       F       F       F       F
Bank Sta=3151.05,3180.04
XS Rating Curve= 0
Exp/Cntr=.5,.3

Type RM Length L Ch R = 1 ,9307.397,504.63,501.88,508.1
BEGIN DESCRIPTION:
Cross Section Obtained From LIDAR Data, With Channel survey copied from 9463 and interpolated Based on Slope
END DESCRIPTION:
XS GIS Cut Line= 6
     3103606.901    13825448.571     3100720.694    13825325.506
     3100622.543    13825356.608      3100306.32     13825349.38
      3100189.78    13825316.159     3097992.417    13825225.467
#Sta/Elev= 30
       0    50.3  435.19   48.27 1343.56   48.42 1689.88   50.84 1733.92   49.08
 2093.18   48.63 2199.34   50.46 2755.55   51.06  2814.9    49.2 2844.93   51.05
  3089.8   51.32 3111.11    50.9 3128.92   47.49 3141.88   47.37 3150.38   41.71
 3150.52    39.7 3155.35   39.26 3159.79   39.56 3160.36   41.72 3168.85   46.72
 3170.76   47.84 3194.83    50.1 3377.11   49.26 4375.53   50.34 4474.93   47.67
 4519.07   49.69  4715.6   50.31 5148.27    49.1 5369.71   51.73 5628.52   51.13
#Mann= 4 ,-1 , 0
       0      .1       0 3128.92    .015       0 3168.85     .09       0
 3377.11      .1       0
#XS Ineff= 4 ,-1
       0 3077.38   51.31 3212.35 3428.09   50.29 3762.89 4939.13   50.74
 4944.72 5262.15   50.86
Permanent Ineff=
       F       F       F       F
Bank Sta=3141.88,3170.76
XS Rating Curve= 0
Exp/Cntr=.3,.1

Type RM Length L Ch R = 1 ,8805.521,52.64,53.15,88.01
XS GIS Cut Line= 5
     3103194.512    13824890.975     3100639.135    13824854.011
     3100323.722    13824848.898     3100203.972    13824846.925
     3098013.829    13824823.404
#Sta/Elev= 30
       0   47.49  900.05   47.39 1011.29   49.94 1254.84   49.22 1305.09   47.68
 1575.32   49.62 1665.13   47.59 1710.13   50.49 1915.84   51.05 2025.17   48.03
 2107.26    50.6 2315.24   50.46  2385.2   47.56 2445.21    50.7    2557   50.52
 2642.13   50.69 2703.23   48.02 2704.98    46.2 2710.32   38.71 2724.27   38.56
 2731.09   46.14 2733.43   48.75 2926.94   47.98 3024.27   50.34 3075.28   49.58
 3137.88    50.9 3934.68   49.84 4035.34   47.35 4575.37    49.6 5181.13   48.55
#Mann= 5 ,-1 , 0
       0      .1       0    2557      .1       0 2704.98    .015       0
 2731.09     .09       0 2926.94      .1       0
#XS Ineff= 4 ,-1
 -102.08 1905.48   51.09 1949.91 2621.45   50.79 2758.08 2989.74   49.19
 3392.22 5310.93   50.85
Permanent Ineff=
       F       F       F       F
Bank Sta=2703.23,2733.43
XS Rating Curve= 0
Exp/Cntr=.5,.3

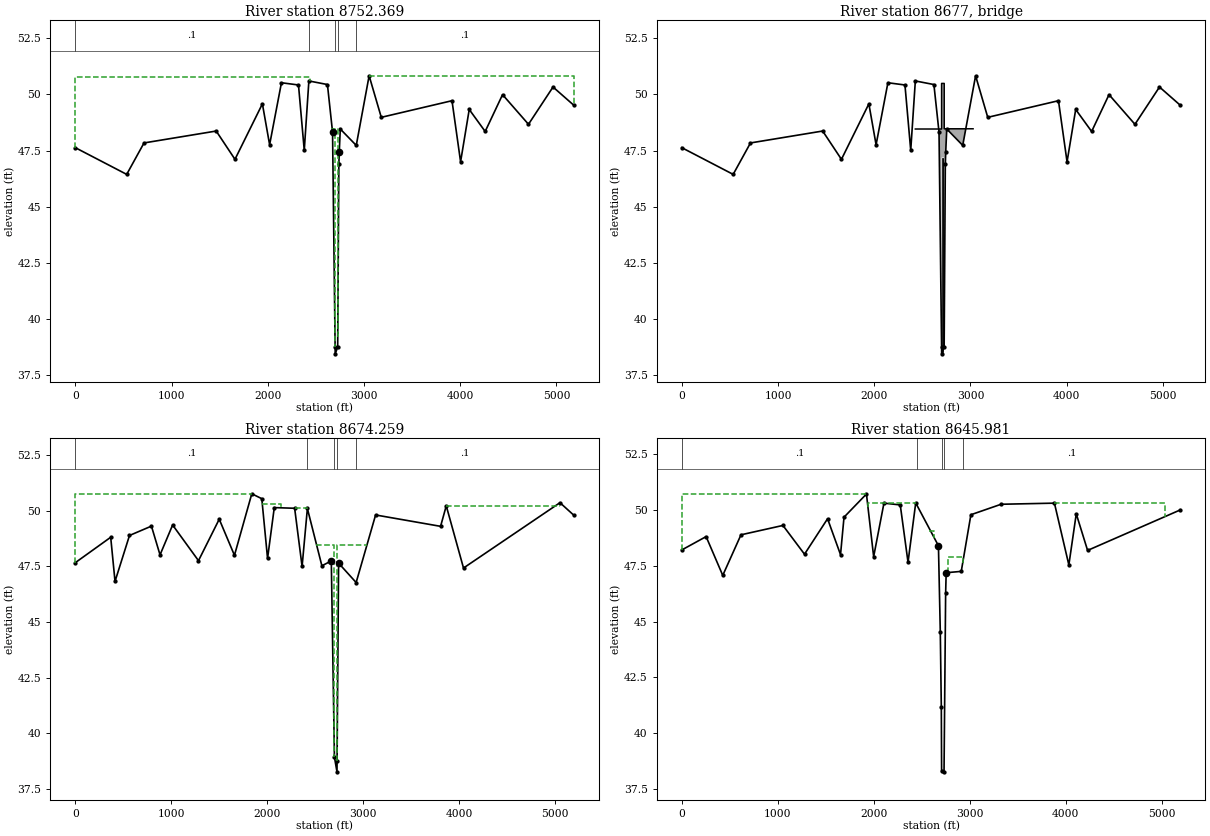
Type RM Length L Ch R = 1 ,8752.369,78.21,78.11,84.86
XS GIS Cut Line= 6
     3103188.704    13824827.084     3100762.755    13824835.719
     3100643.319    13824802.178     3100319.771    13824794.508
     3100257.792    13824793.974      3098011.45    13824790.096
#Sta/Elev= 30
       0   47.63  534.15   46.44  714.15   47.84 1464.16   48.37 1659.16   47.11
 1944.16   49.58 2019.16   47.76 2142.03   50.52 2319.16   50.42 2379.16   47.51
    2427    50.6 2619.91   50.44 2673.14   48.32 2699.81   38.75 2700.63   38.45
 2726.43   38.75 2738.52   46.89 2742.86   47.45 2753.53   48.46 2919.39   47.73
 3053.12   50.83 3179.36   48.98 3914.18   49.72 4003.43      47 4093.28   49.33
 4258.88   48.35 4439.48   49.99 4708.88   48.67 4963.88   50.33 5181.99   49.51
#Mann= 5 ,-1 , 0
       0      .1       0    2427      .1       0 2699.81    .015       0
 2726.43     .09       0 2919.39      .1       0
#XS Ineff= 4 ,-1
 -174.23 2434.68   50.78 2670.93 2699.82   48.46 2727.13 2753.54   48.47
    3053 5249.61   50.83
Permanent Ineff=
       F       F       F       F
Bank Sta=2673.14,2742.86
XS Rating Curve= 0
Exp/Cntr=.8,.6

Type RM Length L Ch R = 3 ,8677    ,,,
BEGIN DESCRIPTION:
S9 Bridge
END DESCRIPTION:
Bridge Culvert--1,0,-1,-1, 0
Deck Dist Width WeirC Skew NumUp NumDn MinLoCord MaxHiCord MaxSubmerge Is_Ogee
9,60.2,2.6,0, 7, 7, , , .95, 0, 0,0,,
    2427 2677.21 2699.82 2699.83 2727.12 2727.13    3027
   48.46   48.46   48.46   50.49   50.49   48.47   48.47
      38      38      38   47.19   47.19      38      38
    2420 2679.64 2702.25 2702.26 2729.55 2729.56    3020
   48.46   48.46   48.46   50.49   50.49   48.47   48.47
      38      38      38   47.19   47.19      38      38
Pier Skew, UpSta & Num, DnSta & Num=  ,2709.18, 2 ,2712.68, 2 , 0 , 0 , 0 ,,
      .7      .7
   38.43   47.19
      .7      .7
   38.43   47.19
Pier Skew, UpSta & Num, DnSta & Num=  ,2717.88, 2 ,2721.38, 2 , 0 , 0 , 0 ,,
      .7      .7
   38.43   47.19
      .7      .7
   38.43   47.19
BR Coef=-1 , 1 , 1 ,1.25, 0 ,,,.8,0,2,0,
WSPro=,,,, 1 ,,,, 0 ,,,, 0 ,,,,-1 ,-1 ,-1 , 0 , 0 , 0 , 0 , 0
BC Design=,, 0 ,, 0 ,,,,,,
BC HTab HWMax=50.83

Type RM Length L Ch R = 1 ,8674.259,28.34,28.28,28.28
XS GIS Cut Line= 6
     3103188.704    13824716.726     3100764.251    13824659.426
     3100642.737    13824723.848     3100258.886     13824715.66
      3100108.61    13824644.112     3098023.345    13824556.947
#Sta/Elev= 30
       0   47.66  369.25    48.8  414.26   46.82   565.1   48.88  793.98    49.3
  883.53   48.01 1014.92   49.35 1284.51   47.75 1500.88   49.61 1659.61   47.99
 1840.32   50.75 1944.69   50.53 2004.71   47.85 2074.85   50.13 2287.23    50.1
 2364.81   47.49    2420   50.09 2571.22   47.52 2669.39   47.74 2702.04   38.94
 2728.72   38.28 2729.56   38.75 2745.47   47.64 2928.36   46.77 3131.35    49.8
 3808.94   49.29 3868.02   50.21 4047.91   47.42 5053.79   50.35 5200.13   49.78
#Mann= 5 ,-1 , 0
       0      .1       0    2420      .1       0 2702.04    .015       0
 2729.56     .09       0 2928.36      .1       0
#XS Ineff= 6 ,-1
 -209.99  1839.1   50.75  1945.7 2145.61   50.29 2286.29 2419.57   50.09
    2515    2702   48.46 2729.56 3046.66   48.47 3867.79 5049.26   50.21
Permanent Ineff=
       F       F       F       F       F       F
Bank Sta=2669.39,2745.47
XS Rating Curve= 0
Exp/Cntr=.8,.6

Type RM Length L Ch R = 1 ,8645.981,915.7,915.76,918
BEGIN DESCRIPTION:
Survey Data Used for Points from Station 147.78 to 172.91.  All other Points obtained from LIDAR data.
END DESCRIPTION:
XS GIS Cut Line= 6
     3103182.896     13824670.26     3100738.453    13824639.431
     3100645.527    13824695.491      3100319.19    13824688.518
     3100145.848    13824600.173     3098028.103    13824506.986
#Sta/Elev= 30
       0   48.21  253.62   48.81  427.02   47.07  616.76   48.89 1053.73   49.31
 1278.44   48.02 1518.46   49.61 1653.47      48 1689.84   49.68 1923.49   50.72
  1998.5   47.91 2105.75   50.31 2275.51   50.23 2356.49   47.66 2436.58   50.32
 2673.17    48.4 2692.52   44.54 2703.18   41.15 2706.31   38.28 2731.43   38.26
 2748.19   46.28 2753.84   47.19 2910.84   47.25  3011.2   49.79 3325.67   50.26
  3881.2   50.31 4031.35   47.54 4108.54   49.83 4226.54   48.19 5193.93   50.01
#Mann= 5 ,-1 , 0
       0      .1       0    2450      .1       0 2708.09    .015       0
 2733.27     .09       0 2928.42      .1       0
#XS Ineff= 6 ,-1
  -73.73 1922.49   50.73 1938.72 2437.23   50.33 2575.75 2628.14   49.07
 2769.23 2926.52    47.9 3325.98 3866.49   50.26 3880.97 5029.12   50.31
Permanent Ineff=
       F       F       F       F       F       F
Bank Sta=2673.17,2753.84
XS Rating Curve= 0
Exp/Cntr=.3,.1