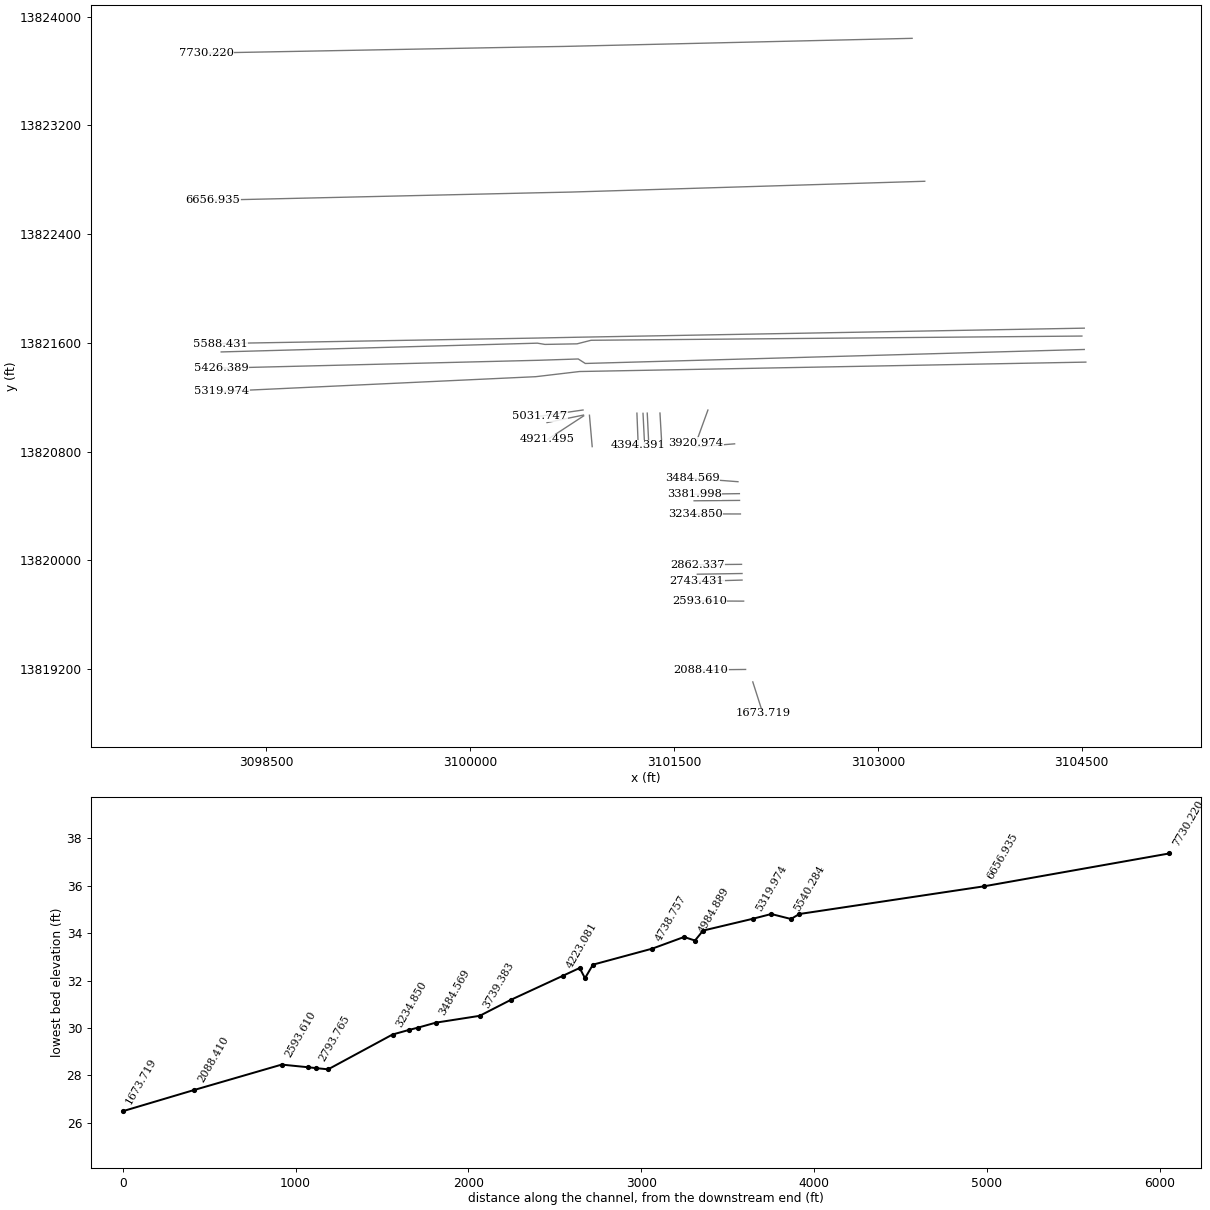
HEC-RAS study D111-00-00.prj: D111-00-00

--- D111-00-00.g01 (geometry) --- (continued)

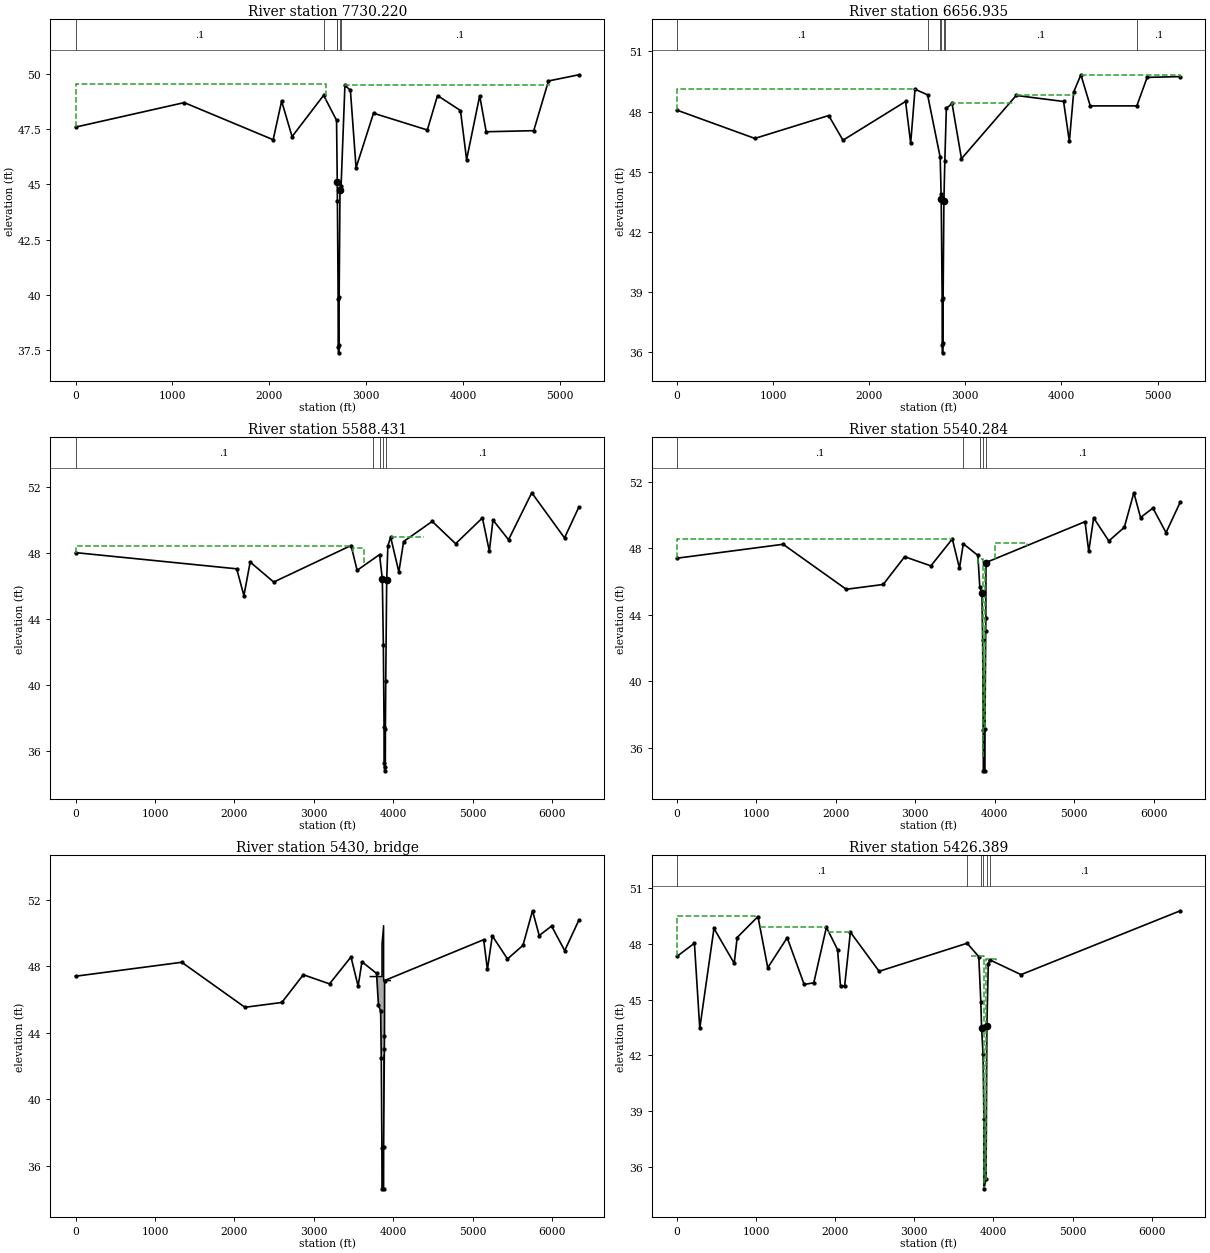
Type RM Length L Ch R = 1 ,7730.220,1073.05,1073.29,1073.26
XS GIS Cut Line= 4
     3103252.595    13823839.674     3100690.619    13823780.168
     3100436.622    13823775.941      3098061.41    13823731.408
#Sta/Elev= 30
       0   47.59 1121.37    48.7 2038.59   47.02 2125.88   48.77 2233.64   47.16
    2559   49.03  2692.5    47.9 2699.92    45.1 2701.26   44.26 2708.87    39.8
 2709.46   37.65 2713.91   37.37 2718.71   37.73 2719.19   39.91 2728.13   44.76
  2729.2   44.77 2739.36   44.94 2778.74   49.48 2835.28   49.26 2893.78   45.75
 3073.81   48.22 3628.91   47.46 3733.93   49.02  3970.7   48.34 4033.98   46.12
    4169   49.01 4235.77   47.38 4726.54   47.43 4878.55   49.68 5192.33   49.96
#Mann= 6 ,-1 , 0
       0      .1       0    2559      .1       0  2692.5     .08       0
 2701.26    .015       0  2729.2     .08       0 2739.36      .1       0
#XS Ineff= 2 ,-1
 -128.31 2582.48   49.54 2778.65 4895.85   49.48
Permanent Ineff=
       F       F
Bank Sta=2699.92,2728.13
XS Rating Curve= 0
Exp/Cntr=.3,.1

Type RM Length L Ch R = 1 ,6656.935,1068.91,1068.5,1068.99
XS GIS Cut Line= 4
     3103345.528    13822788.374     3100740.941    13822708.882
      3100480.89    13822703.329     3098111.371    13822648.928
#Sta/Elev= 30
       0   48.07  811.35   46.66 1579.32    47.8 1727.73   46.57 2378.86    48.5
  2432.1   46.42 2477.12   49.11    2608   48.83 2739.09   45.72 2748.46   43.89
 2749.71   43.64 2759.64   38.62 2760.33   36.38 2763.41   35.98 2768.85   36.45
  2769.6   38.71 2777.59   43.56 2787.48   45.56 2803.08   48.16 2862.35    48.4
 2960.48   45.65 3529.66    48.8 4022.55    48.5 4082.56   46.51 4127.58   48.97
  4202.6   49.83 4299.79   48.28 4784.46   48.28 4891.66    49.7 5236.06   49.74
#Mann= 7 ,-1 , 0
       0      .1       0    2608      .1       0 2739.09     .08       0
 2748.46    .015       0 2777.07     .08       0 2787.48      .1       0
 4784.46      .1       0
#XS Ineff= 4 ,-1
  -29.96 2476.66    49.1 2865.53 3516.15   48.41 3529.68 4136.32    48.8
 4202.66 5292.68   49.83
Permanent Ineff=
       F       F       F       F
Bank Sta=2749.71,2777.59
XS Rating Curve= 0
Exp/Cntr=.3,.1

Type RM Length L Ch R = 1 ,5588.431,65.63,48.15,51.03
BEGIN DESCRIPTION:
Survey Data Used for Points from Station 113.99 to 172.91.  All other Points obtained from LIDAR data.
END DESCRIPTION:
XS GIS Cut Line= 4
     3104518.802    13821708.032     3100783.592    13821641.082
     3100481.893    13821635.039      3098163.71    13821594.998
#Sta/Elev= 30
       0   48.01 2028.67   47.03 2119.59   45.41 2198.55   47.44 2494.65   46.23
 3468.16   48.44 3544.82   46.94  3826.7   47.89 3861.96   46.41 3874.69   42.44
 3883.67   37.44 3884.01    35.3 3891.58   34.81 3899.69   35.05  3900.5   37.32
 3904.97   40.27 3916.72   46.34 3931.73   48.42 3967.04   48.94 4069.91   46.84
 4129.92   48.68 4489.97    49.9 4784.57   48.55 5121.93   50.11 5208.97    48.1
 5255.09   49.98 5450.77   48.79 5743.16   51.63 6155.22    48.9 6336.37   50.77
#Mann= 5 ,-1 , 0
       0      .1       0    3739      .1       0 3835.56     .04       0
 3874.79    .015       0 3904.97      .1       0
#XS Ineff= 3 ,-1
  -77.68 3468.63   48.44 3487.55 3633.52    48.3 3967.48  4382.4   48.95
Permanent Ineff=
       F       F       F
Bank Sta=3861.96,3916.72
XS Rating Curve= 0
Exp/Cntr=.5,.3

Type RM Length L Ch R = 1 ,5540.284,119.82,113.89,116.54
BEGIN DESCRIPTION:
Survey Data Used for Points from Station 129.09 to 179.13.  All other Points obtained from LIDAR data.
END DESCRIPTION:
XS GIS Cut Line= 6
     3104501.377    13821649.949     3100891.182    13821618.889
     3100788.357    13821592.736      3100552.14    13821588.441
       3100496.3    13821597.616     3098170.848    13821533.142
#Sta/Elev= 30
       0    47.4 1336.87   48.24  2131.9   45.53 2596.94   45.82 2866.92   47.49
 3196.94   46.94 3466.95   48.56 3556.95    46.8    3605   48.27 3788.56   47.57
 3812.45   45.69 3840.19   45.28 3848.36   42.45 3856.27   37.03 3857.39   34.62
 3877.31    34.6 3877.92   37.12 3886.85   42.99 3888.51   43.79 3890.23   47.14
 5137.06    49.6 5183.99   47.81 5245.72   49.83 5436.56   48.44 5631.64   49.26
 5751.68   51.34 5836.12   49.85 5991.78   50.42 6156.84   48.94 6335.62   50.78
#Mann= 5 ,-1 , 0
       0      .1       0    3605      .1       0 3812.45     .04       0
 3848.36    .015       0 3886.85      .1       0
#XS Ineff= 4 ,-1
       0 3466.97   48.56 3794.78    3857   47.38    3878 3891.48   47.15
 3999.82  4404.6   48.31
Permanent Ineff=
       F       F       F       F
Bank Sta=3840.19,3890.23
XS Rating Curve= 0
Exp/Cntr=.5,.3

Type RM Length L Ch R = 3 ,5430    ,,,
BEGIN DESCRIPTION:
S11 Bridge
END DESCRIPTION:
Bridge Culvert--1,0,-1,-1, 0
Deck Dist Width WeirC Skew NumUp NumDn MinLoCord MaxHiCord MaxSubmerge Is_Ogee
32,50,2.6,0, 9, 9, , , .95, 0, 0,0,,
    3711 3840.08 3840.09 3857.29  3857.3 3877.83 3877.84 3890.13    3961
   47.38   47.38   47.38   47.38   49.36   50.44   47.14   47.14   47.14
      34      34      34      34   42.46   42.99      34      34      34
    3669 3865.73 3865.74 3882.94 3882.95 3903.48 3903.49 3915.78 4020.74
   47.38   47.38   47.38   47.38   49.36   50.44   47.14   47.14   47.14
      34      34      34      34   42.46   42.99      34      34      34
Pier Skew, UpSta & Num, DnSta & Num=  ,3868, 2 ,3893, 2 , 0 , 0 , 0 ,,
      .8      .8
   34.44   42.99
      .8      .8
   34.44   42.99
BR Coef=-1 , 1 , 1 ,1.25, 0 ,,,.8,0,2,0,
WSPro=,,,, 1 ,,,, 0 ,,,, 0 ,,,,-1 ,-1 ,-1 , 0 , 0 , 0 , 0 , 0
BC Design=,, 0 ,, 0 ,,,,,,
BC HTab HWMax=48.3

Type RM Length L Ch R = 1 ,5426.389,100.05,106.42,111.71
BEGIN DESCRIPTION:
Survey Data Used for Points from Station 201.33 to 249.96.  All other Points obtained from LIDAR data.
END DESCRIPTION:
XS GIS Cut Line= 5
     3104518.802    13821551.208     3100848.749    13821448.339
     3100796.841      13821481.4     3100504.807    13821471.723
     3098170.848    13821414.188
#Sta/Elev= 30
       0   47.33  221.75   48.04  289.36   43.46  468.94   48.84  724.53   46.96
  761.83   48.35 1024.65   49.48 1148.24   46.72 1393.93   48.34 1608.44   45.82
 1729.92   45.91  1889.3    48.9 2030.04    47.7  2067.9   45.72 2120.08   45.75
 2192.31   48.64 2555.25   46.53    3667   48.04 3814.53   47.32 3840.33   44.88
 3849.96   43.48 3868.63   42.06 3879.05   38.58 3879.43   34.81 3906.74   35.35
 3916.96    43.6 3934.59   46.92 3951.64   47.15 4348.22   46.35  6359.9   49.79
#Mann= 6 ,-1 , 0
       0      .1       0    3667      .1       0 3840.33     .04       0
 3868.63    .015       0 3916.96     .04       0 3951.64      .1       0
#XS Ineff= 5 ,-1
  -72.77  992.54    49.5 1044.05  1889.5   48.91 1903.91 2192.07   48.64
    3713    3883   47.38    3904  4029.7   47.18
Permanent Ineff=
       F       F       F       F       F
Bank Sta=3849.96,3916.96
XS Rating Curve= 0
Exp/Cntr=.5,.3

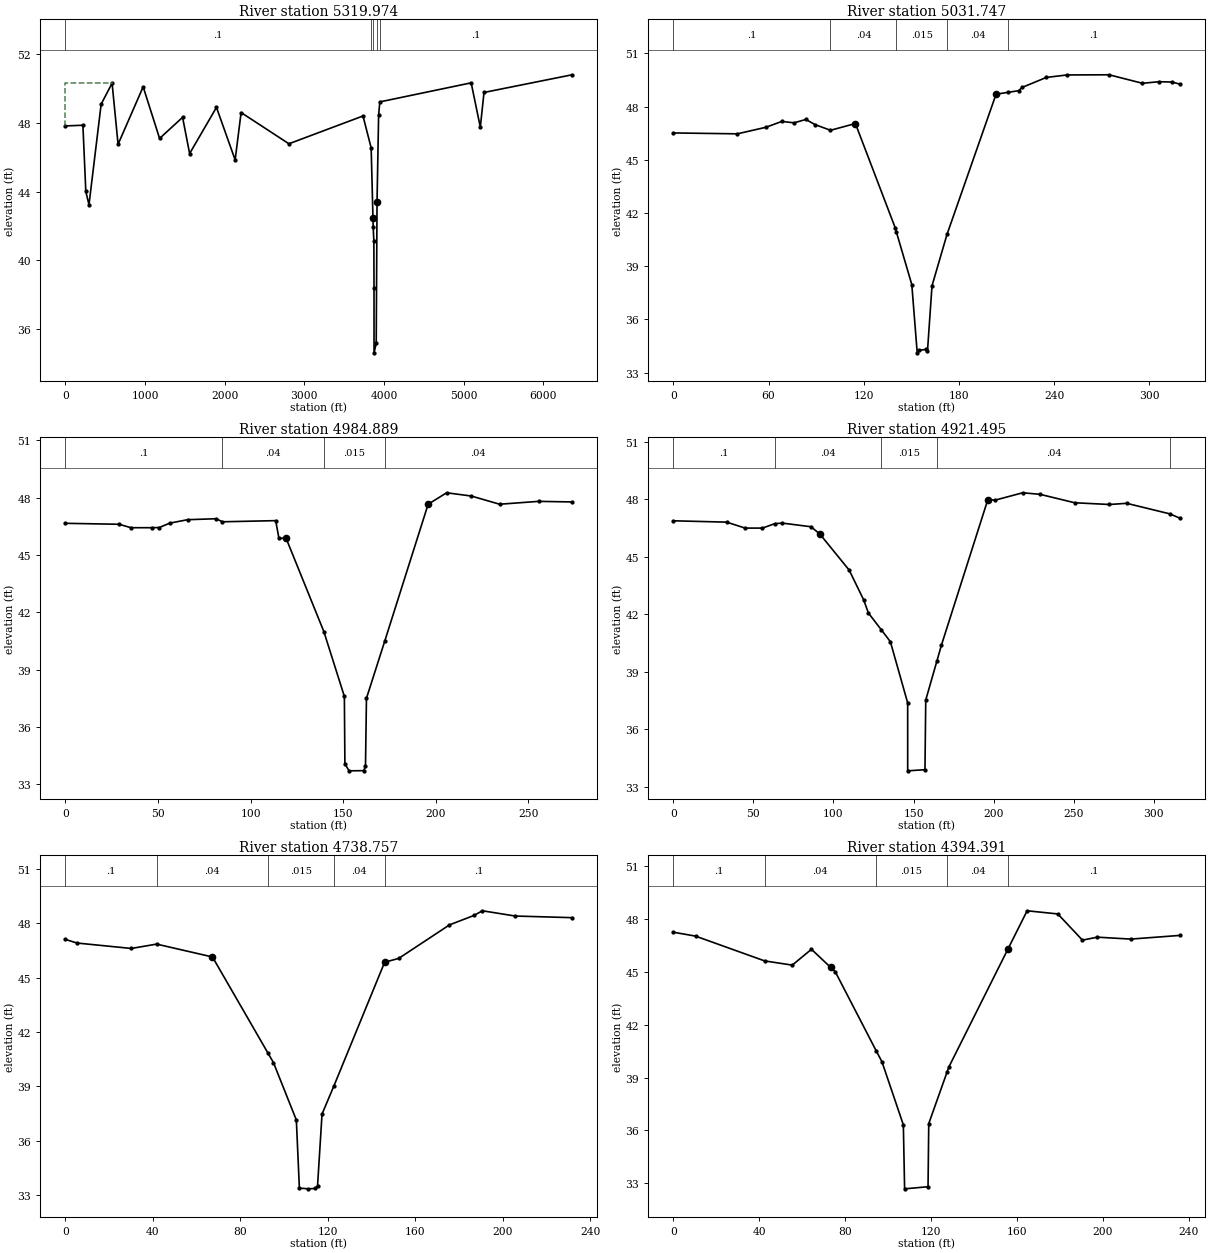
Type RM Length L Ch R = 1 ,5319.974,287.25,288.23,290.77
BEGIN DESCRIPTION:
Cross Section copied with survey data taken from section  5426.389. Overbanks obtained From LIDAR Data, With Channel Interpolated Based on Slope.
END DESCRIPTION:
XS GIS Cut Line= 4
     3104530.419    13821458.275     3100806.253    13821389.065
     3100484.609    13821351.118     3098173.227    13821242.895
#Sta/Elev= 30
       0   47.83  219.28   47.87  255.91   44.01  295.71   43.24  448.58    49.1
  585.96   50.32  660.98   46.76  976.03   50.11 1182.34    47.1 1471.12   48.33
 1559.49   46.22 1896.64   48.91 2131.23   45.85 2205.95   48.61 2806.35   46.79
 3736.87   48.41 3839.22   46.55  3862.1   42.45 3864.38   41.97 3873.12   41.13
  3875.1   38.39 3875.48   34.61 3902.79   35.16 3913.02   43.41 3932.94   48.46
 3948.04   49.23 5095.08   50.34 5210.01   47.76 5256.54   49.78  6362.6   50.81
#Mann= 5 ,-1 , 0
       0      .1       0 3839.22     .04       0 3864.38    .015       0
 3913.02     .04       0 3948.04      .1       0
#XS Ineff= 1 ,-1
 -245.61  586.78   50.32
Permanent Ineff=
       F
Bank Sta=3862.1,3913.02
XS Rating Curve= 0
Exp/Cntr=.3,.1

Type RM Length L Ch R = 1 ,5031.747,43.87,46.86,51.68
BEGIN DESCRIPTION:
Survey Data Used for Points from Station 114.73 to 203.38.  All other Points obtained from LIDAR data.
END DESCRIPTION:
XS GIS Cut Line= 2
     3100832.199    13821106.095     3100516.089    13821060.305
#Sta/Elev= 29
       0   46.51   40.33   46.46   58.32   46.83   68.35   47.16   76.04   47.08
    83.5   47.27   89.28   46.98   99.02   46.66  114.73   47.04  139.78   41.17
  140.54   40.93  150.28   37.96  153.69   34.11  154.96   34.26  159.42    34.3
  160.17   34.22  163.02   37.89  172.48   40.79  203.38   48.69  210.81    48.8
  217.57   48.89  219.91   49.08  235.07   49.64  248.15   49.78  274.62   49.79
   295.7   49.31  306.19    49.4  314.34   49.38  319.41   49.26
#Mann= 5 ,-1 , 0
       0      .1       0   99.02     .04       0  140.54    .015       0
  172.48     .04       0  210.81      .1       0
Bank Sta=114.73,203.38
XS Rating Curve= 0
Exp/Cntr=.3,.1

Type RM Length L Ch R = 1 ,4984.889,41.67,63.39,95.02
BEGIN DESCRIPTION:
Survey Data Used for Points from Station 113.56 to 205.89.  All other Points obtained from LIDAR data.
END DESCRIPTION:
XS GIS Cut Line= 2
     3100835.569    13821068.905     3100567.573    13821013.586
#Sta/Elev= 26
       0   46.66   28.96   46.61   35.39   46.43   46.91   46.43   50.71   46.44
   56.37   46.67   66.03   46.85   81.34    46.9   84.83   46.74  113.56    46.8
  115.32   45.87  119.12   45.89  139.56   40.99  150.65   37.59  150.94   34.05
  153.21   33.69  161.14    33.7  162.06   33.93  162.58   37.49   172.4   40.47
   195.9   47.66  205.89   48.26  219.19   48.09  234.51   47.66  255.51   47.81
  273.65   47.78
#Mann= 4 ,-1 , 0
       0      .1       0   84.83     .04       0  139.56    .015       0
   172.4     .04       0
Bank Sta=119.12,195.9
XS Rating Curve= 0
Exp/Cntr=.3,.1

Type RM Length L Ch R = 1 ,4921.495,117.48,182.74,267.98
BEGIN DESCRIPTION:
Survey Data Used for Points from Station 135.55 to 196.42.  All other Points obtained from LIDAR data.
END DESCRIPTION:
XS GIS Cut Line= 2
     3100836.499     13821062.63     3100571.524    13820889.467
#Sta/Elev= 28
       0   46.87   33.28    46.8   44.79   46.49   55.62   46.49   63.31   46.72
   68.02   46.75   85.94   46.56   91.49   46.18  109.81    44.3  118.91   42.74
  121.78   42.07  129.78    41.2  135.54   40.57  146.35   37.38  146.36   33.84
  157.16    33.9  157.64   37.53   164.6   39.56   167.4   40.38  196.42   47.97
  201.17   47.95  218.18   48.33  229.01   48.25  250.69   47.81  272.36   47.72
   283.2   47.78  310.21   47.23  316.54      47
#Mann= 5 ,-1 , 0
       0      .1       0   63.31     .04       0  129.78    .015       0
   164.6     .04       0  310.21      .1       0
Bank Sta=91.49,196.42
XS Rating Curve= 0
Exp/Cntr=.3,.1

Type RM Length L Ch R = 1 ,4738.757,346.96,344.37,340.81
BEGIN DESCRIPTION:
Survey Data Used for Points from Station 67.24 to 146.09.  All other Points obtained from LIDAR data.
END DESCRIPTION:
XS GIS Cut Line= 2
     3100879.383    13821067.511     3100899.604    13820836.704
#Sta/Elev= 21
       0   47.12    5.23   46.92   30.13   46.62    41.7   46.86   67.24   46.15
   92.68   40.83   95.12   40.32  105.59   37.15  106.98   33.39  111.06   33.35
  114.15   33.37  115.29   33.52  117.34   37.48   122.8   39.04  145.97   45.86
  152.39   46.07   175.6   47.92  186.77   48.44  190.66    48.7  205.71   48.41
  231.69   48.32
#Mann= 5 ,-1 , 0
       0      .1       0    41.7     .04       0   92.68    .015       0
   122.8     .04       0  145.97      .1       0
Bank Sta=67.24,145.97
XS Rating Curve= 0
Exp/Cntr=.3,.1

Type RM Length L Ch R = 1 ,4394.391,45.24,45.81,46.55
BEGIN DESCRIPTION:
Survey Data Used for Points from Station 64.26 to 178.95.  All other Points obtained from LIDAR data.
END DESCRIPTION:
XS GIS Cut Line= 2
     3101228.498    13821082.851     3101238.028    13820847.164
#Sta/Elev= 22
       0   47.26   10.28   47.04   42.46   45.63   55.32   45.39   64.26   46.29
   73.21   45.26   75.37   45.01   94.35   40.53    97.1   39.89  107.04   36.31
  107.63   32.67  118.54   32.79  118.87   36.38  127.37    39.3  128.32   39.62
  155.68   46.29  164.67   48.48  178.95    48.3  190.43   46.81  197.35   46.98
   212.9   46.87  235.88   47.08
#Mann= 5 ,-1 , 0
       0      .1       0   42.46     .04       0   94.35    .015       0
  127.37     .04       0  155.68      .1       0
Bank Sta=73.21,155.68
XS Rating Curve= 0
Exp/Cntr=.5,.3

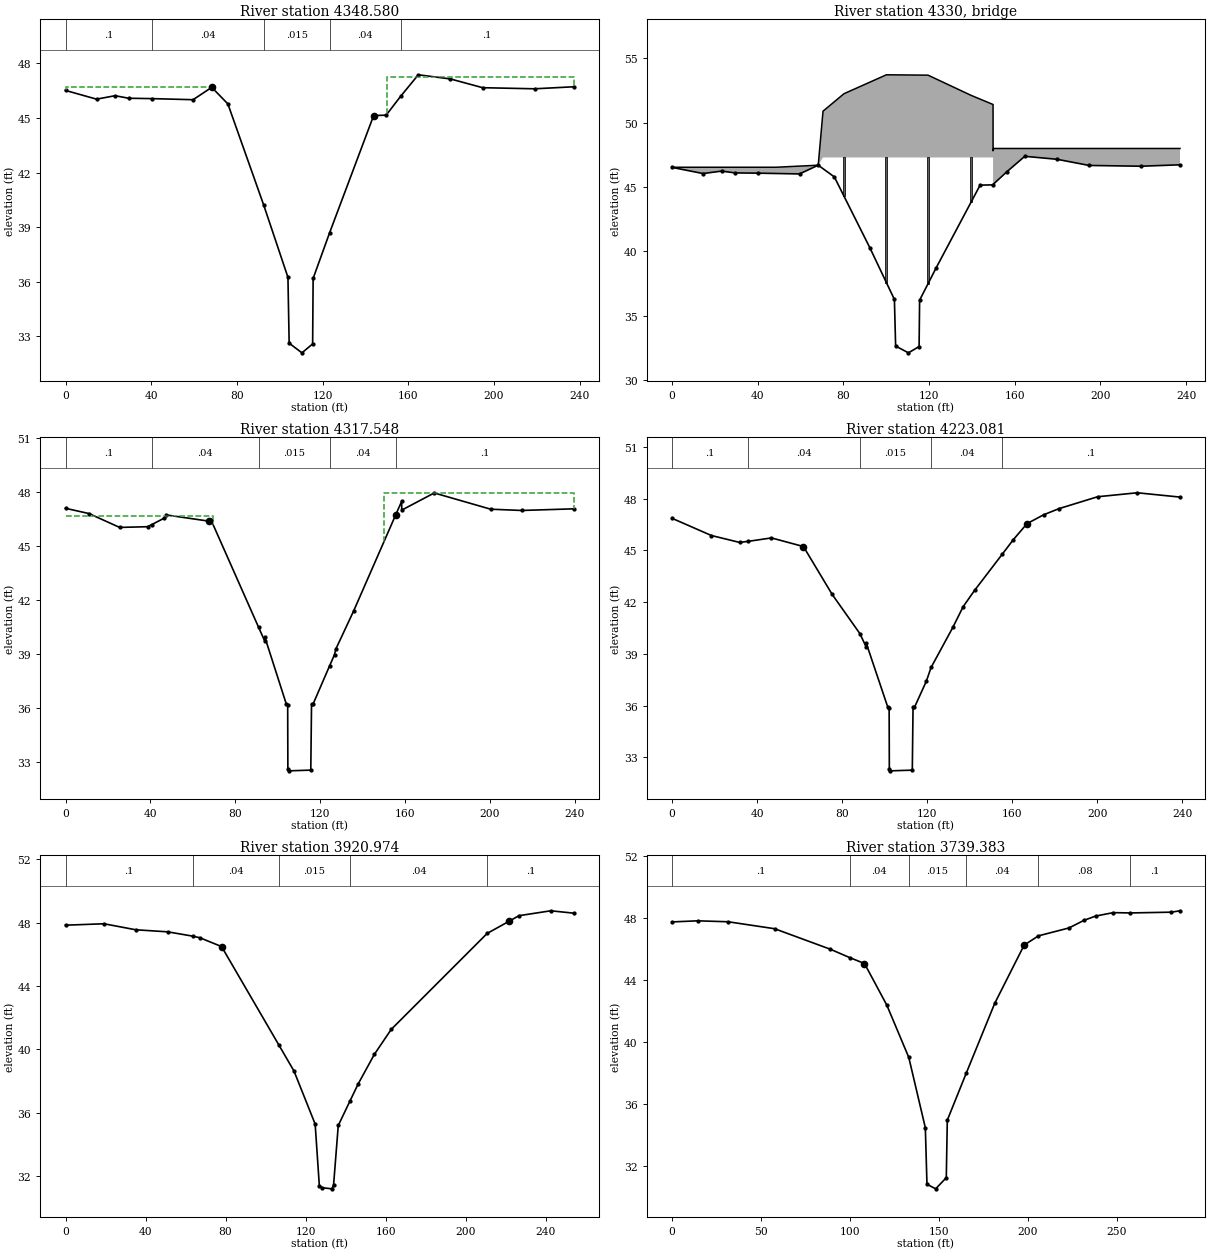
Type RM Length L Ch R = 1 ,4348.580,31.12,31.03,30.92
BEGIN DESCRIPTION:
Survey Data Used for Points from Station 68.26 to 149.17.  All other Points obtained from LIDAR data.
END DESCRIPTION:
XS GIS Cut Line= 2
     3101273.358    13821081.457     3101285.212    13820844.607
#Sta/Elev= 23
       0   46.52   14.51   46.04   23.12   46.23   29.52   46.09   40.31   46.07
   59.56   46.01   68.26   46.69   75.79   45.78   92.49   40.23  103.83   36.25
   104.4   32.63  110.37    32.1  115.36   32.59  115.59   36.19  123.32   38.71
  143.84   45.14  149.67   45.16  156.39   46.19  164.69   47.38  179.71   47.15
  194.73   46.67  218.96   46.61  237.15   46.72
#Mann= 5 ,-1 , 0
       0      .1       0   40.31     .04       0   92.49    .015       0
  123.32     .04       0  156.39      .1       0
#XS Ineff= 2 , 0
       0      70   46.69     150       0   47.27
Permanent Ineff=
       F       F
Bank Sta=68.26,143.84
XS Rating Curve= 0
Exp/Cntr=.5,.3

Type RM Length L Ch R = 3 ,4330    ,,,
BEGIN DESCRIPTION:
S13 Walkway
END DESCRIPTION:
Bridge Culvert--1,0,-1,-1, 0
Deck Dist Width WeirC Skew NumUp NumDn MinLoCord MaxHiCord MaxSubmerge Is_Ogee
13,5,2.6,0, 12, 12, , , .95, 0, 0,0,,
       0    48.5   68.26   70.51    80.3  100.11  119.54  139.63  149.88  149.89
  150.16  237.15
   46.53   46.53   46.69   50.89   52.25   53.72   53.69   52.12   51.41   47.81
   47.99   47.99
      30      30      30   47.29   47.29   47.29   47.29   47.29   47.29      30
      30      30
       0    48.5   68.26   70.51    80.3  100.11  119.54  139.63  149.88  149.89
  150.16  239.46
   46.53   46.53   46.69   50.89   52.25   53.72   53.69   52.12   51.41   47.81
   47.99   47.99
      30      30      30   47.29   47.29   47.29   47.29   47.29   47.29      30
      30      30
Pier Skew, UpSta & Num, DnSta & Num=  ,80.3, 2 ,80.3, 2 , 0 , 0 , 0 ,,
     .95     .95
      32   50.12
     .95     .95
      32   50.12
Pier Skew, UpSta & Num, DnSta & Num=  ,100.11, 2 ,100.11, 2 , 0 , 0 , 0 ,,
     .95     .95
      32   50.12
     .95     .95
      32   50.12
Pier Skew, UpSta & Num, DnSta & Num=  ,119.54, 2 ,119.54, 2 , 0 , 0 , 0 ,,
     .95     .95
      32   50.12
     .95     .95
      32   50.12
Pier Skew, UpSta & Num, DnSta & Num=  ,139.63, 2 ,139.63, 2 , 0 , 0 , 0 ,,
     .95     .95
      32   50.12
     .95     .95
      32   50.12
BR Coef=-1 , 1 , 1 ,1.25, 0 ,,,.8,0,2,0,
WSPro=,,,, 1 ,,,, 0 ,,,, 0 ,,,,-1 ,-1 ,-1 , 0 , 0 , 0 , 0 , 0
BC Design=,, 0 ,, 0 ,,,,,,
BC HTab HWMax=47.38

Type RM Length L Ch R = 1 ,4317.548,93.9,94.47,95.21
BEGIN DESCRIPTION:
Survey Data Used for Points from Station 46.45 to 181.66.  All other Points obtained from LIDAR data.
END DESCRIPTION:
XS GIS Cut Line= 2
     3101304.504    13821083.084     3101316.125     13820843.91
#Sta/Elev= 30
       0   47.08      11   46.79   25.53   46.02   38.72   46.06   40.71   46.18
   46.45   46.53   47.56   46.71   67.46   46.37   68.68   46.41   90.99   40.49
   93.87   39.73   93.93   39.95  104.02   36.25  104.72   36.17  104.81   32.62
  105.35   32.53  115.61   32.57  115.96   36.21  116.61   36.21  124.52   38.36
  126.79   38.97  127.42   39.28  135.77   41.38  155.65   46.72  158.42   47.46
  158.49   46.98   173.8   47.93  200.41   47.03  214.99   46.96  239.46   47.05
#Mann= 5 ,-1 , 0
       0      .1       0   40.71     .04       0   90.99    .015       0
  124.52     .04       0  155.65      .1       0
#XS Ineff= 2 , 0
       0    69.6   46.66     150       0   47.94
Permanent Ineff=
       F       F
Bank Sta=67.46,155.65
XS Rating Curve= 0
Exp/Cntr=.5,.3

Type RM Length L Ch R = 1 ,4223.081,327.95,302.11,270.75
BEGIN DESCRIPTION:
Cross Section Obtained From LIDAR Data, With Channel Interpolated Based on Slope
END DESCRIPTION:
XS GIS Cut Line= 2
     3101398.042    13821083.684     3101411.895    13820845.162
#Sta/Elev= 30
       0   46.87   18.53   45.87   31.77   45.47   35.84   45.53   46.79   45.73
   61.82   45.23   75.34   42.45    88.4   40.17   91.28   39.41   91.34   39.63
  101.43   35.93  102.13   35.85  102.22    32.3  102.76   32.21  113.02   32.25
  113.37   35.89  114.02   35.89  119.65   37.42  121.85   38.21  132.14   40.55
  136.94   41.74  142.34   42.69   155.3   44.78  160.54   45.63  166.99   46.56
  174.74   47.07  182.02   47.43  200.18   48.12  218.81   48.35  238.92    48.1
#Mann= 5 ,-1 , 0
       0      .1       0   35.84     .04       0    88.4    .015       0
  121.85     .04       0   155.3      .1       0
Bank Sta=61.82,166.99
XS Rating Curve= 0
Exp/Cntr=.3,.1

Type RM Length L Ch R = 1 ,3920.974,260.36,181.59,111.6
BEGIN DESCRIPTION:
Survey Data Used for Points from Station 78.02 to 154.38.  All other Points obtained from LIDAR data.
END DESCRIPTION:
XS GIS Cut Line= 2
      3101750.66     13821105.63     3101663.962     13820866.92
#Sta/Elev= 24
       0   47.84    19.2   47.93   35.16   47.55   51.12   47.42   63.49   47.15
   67.08   47.05   78.02   46.49  106.67   40.27  114.22   38.63   124.8   35.28
  126.89   31.39   128.4   31.26  133.17   31.19     134   31.42  136.35   35.19
  142.22   36.74  146.28   37.81  154.38   39.68  162.83   41.26  210.79   47.32
  221.77   48.09  226.67   48.44  242.62   48.75  253.97    48.6
#Mann= 5 ,-1 , 0
       0      .1       0   63.49     .04       0  106.67    .015       0
  142.22     .04       0  210.79      .1       0
Bank Sta=78.02,221.77
XS Rating Curve= 0
Exp/Cntr=.3,.1

Type RM Length L Ch R = 1 ,3739.383,264.84,254.81,248.21
BEGIN DESCRIPTION:
Survey Data Used for Points from Station 108.22 to 206.04.  All other Points obtained from LIDAR data.
END DESCRIPTION:
XS GIS Cut Line= 2
     3101947.066    13820857.158     3101662.335    13820834.845
#Sta/Elev= 25
       0   47.77   14.45   47.84   31.55   47.78   57.69   47.33   89.09      46
   99.96   45.46  108.22   45.08  120.77   42.39  133.12   39.01  142.43   34.46
  143.35   30.81  148.22   30.51  154.21   31.23  154.78   34.95  165.36   37.97
  181.42    42.5  197.98   46.27  206.04   46.87  223.19   47.38  231.75   47.88
  238.24   48.15  248.07   48.37  257.74   48.35  280.72    48.4   285.6   48.49
#Mann= 6 ,-1 , 0
       0      .1       0   99.96     .04       0  133.12    .015       0
  165.36     .04       0  206.04     .08       0  257.74      .1       0
Bank Sta=108.22,197.98
XS Rating Curve= 0
Exp/Cntr=.3,.1

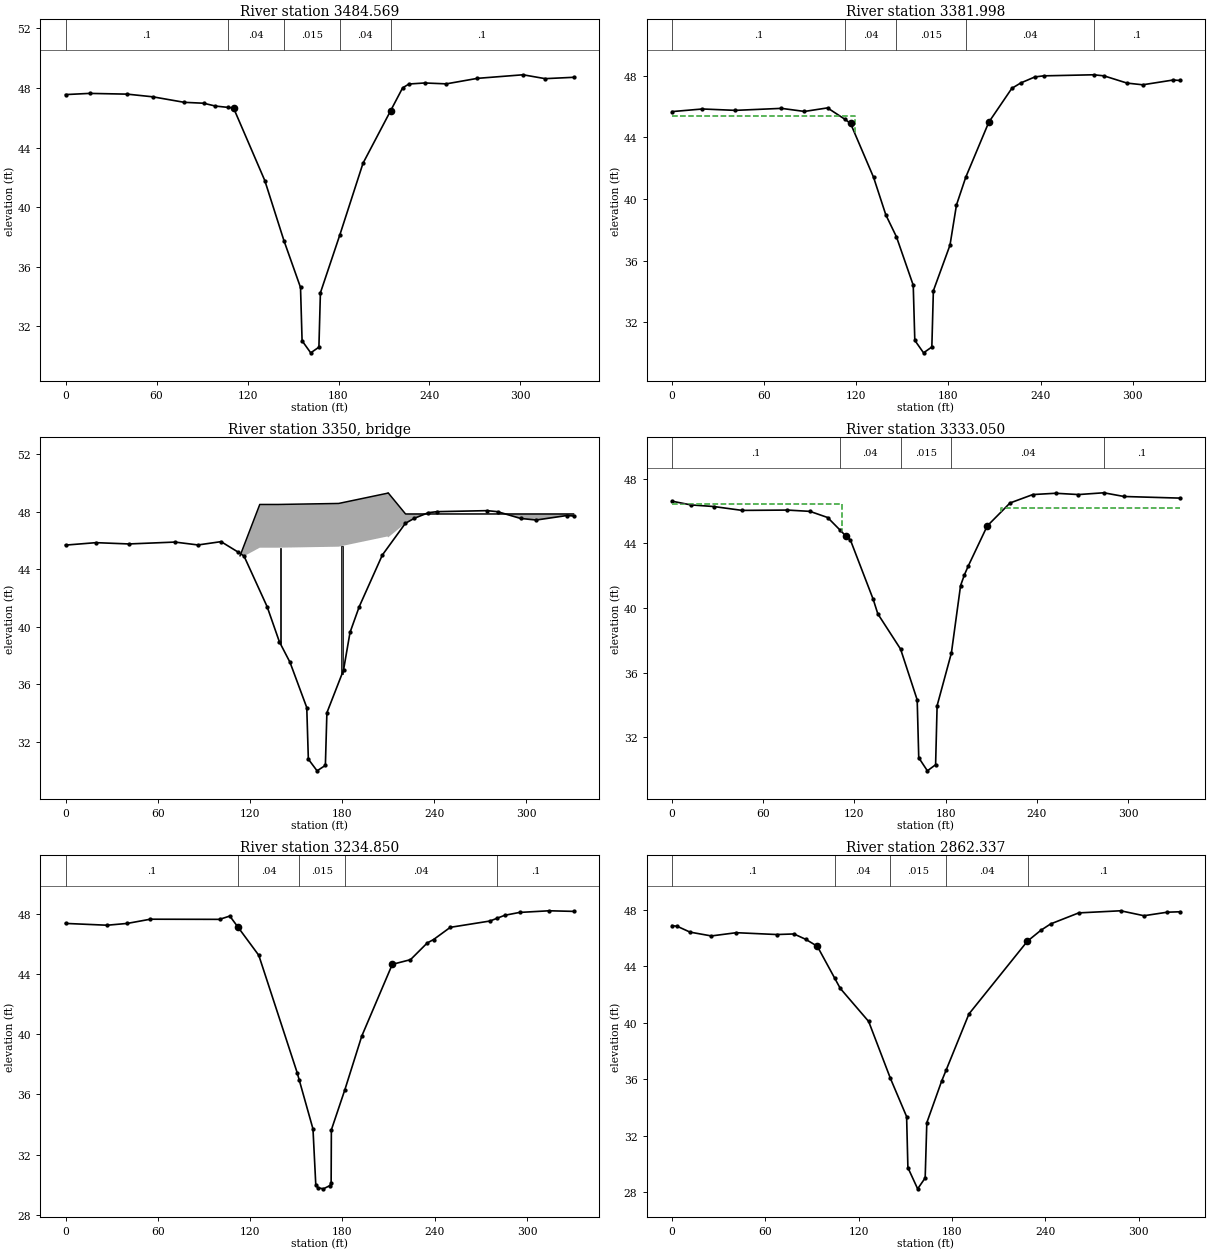
Type RM Length L Ch R = 1 ,3484.569,96.91,102.57,106.57
BEGIN DESCRIPTION:
Survey Data Used for Points from Station 98.80 to 222.27.  All other Points obtained from LIDAR data.
END DESCRIPTION:
XS GIS Cut Line= 2
     3101971.704    13820578.703     3101637.697    13820604.271
#Sta/Elev= 27
       0   47.56   15.85   47.64   40.76   47.59   57.58   47.41   78.32   47.04
   91.06   46.98    98.8   46.79  107.19    46.7  110.79   46.66   131.4   41.79
  144.04   37.75  154.96   34.61  155.99   31.03  161.68   30.22  167.08    30.6
  168.07   34.25  180.89   38.14  196.16   42.95  214.39   46.48  222.27   48.01
  226.46   48.27  236.87   48.34  251.08   48.28  271.59   48.65  301.68   48.89
  316.28   48.63  334.98   48.72
#Mann= 5 ,-1 , 0
       0      .1       0  107.19     .04       0  144.04    .015       0
  180.89     .04       0  214.39      .1       0
Bank Sta=110.79,214.39
XS Rating Curve= 0
Exp/Cntr=.5,.3

Type RM Length L Ch R = 1 ,3381.998,49.25,48.95,48.67
BEGIN DESCRIPTION:
Cross Section Obtained From LIDAR Data, With Channel Interpolated Based on Slope
END DESCRIPTION:
XS GIS Cut Line= 2
     3101982.164    13820490.843     3101651.411    13820486.427
#Sta/Elev= 30
       0   45.67   19.87   45.84   41.26   45.75   71.27   45.88   86.27   45.68
  101.27   45.91  112.47   45.18  116.27    44.9  131.27    41.4  139.26   38.96
  146.16   37.54  157.08    34.4  158.11   30.82   163.8   30.01   169.2   30.39
  170.19   34.04  181.01      37  185.24   39.61  191.28   41.41  206.28   44.98
  221.28   47.18  227.12   47.53  236.28   47.92  241.92   47.99  274.55   48.06
  281.28   47.99  296.29   47.52  306.51   47.41  326.29   47.72  330.78   47.69
#Mann= 5 ,-1 , 0
       0      .1       0  112.47     .04       0  146.16    .015       0
  191.28     .04       0  274.55      .1       0
#XS Ineff= 2 , 0
       0  119.05   45.41  214.83       0   46.21
Permanent Ineff=
       F       F
Bank Sta=116.27,206.28
XS Rating Curve= 0
Exp/Cntr=.5,.3

Type RM Length L Ch R = 3 ,3350    ,,,
BEGIN DESCRIPTION:
S15 Bellefontaine Bridge
END DESCRIPTION:
Bridge Culvert--1,0,-1,-1, 0
Deck Dist Width WeirC Skew NumUp NumDn MinLoCord MaxHiCord MaxSubmerge Is_Ogee
2.5,44,2.6,0, 9, 9, , , .95, 0, 0,0,,
  113.65  126.47  138.24  138.57  177.84  209.63  210.05   221.4  330.78
   44.93   48.49   48.49   48.49   48.56   49.27    49.3   47.83   47.83
      43   45.49   45.49   45.49   45.56   46.27    46.2   45.83   45.83
  105.65  118.47  130.24  130.57  169.84  201.63  202.05   213.4  334.25
   44.93   48.49   48.49   48.49   48.56   49.27    49.3   47.83   47.83
      43   45.49   45.49   45.49   45.56   46.27    46.2   45.83   45.83
Pier Skew, UpSta & Num, DnSta & Num=  ,140, 2 ,140, 2 , 0 , 0 , 0 ,,
       1       1
      40   46.27
       1       1
      40   46.27
Pier Skew, UpSta & Num, DnSta & Num=  ,180, 2 ,180, 2 , 0 , 0 , 0 ,,
       1       1
      40   46.27
       1       1
      40   46.27
BR Coef=-1 , 1 , 1 ,1.25, 0 ,,,.8,0,2,0,
WSPro=,,,, 1 ,,,, 0 ,,,, 0 ,,,,-1 ,-1 ,-1 , 0 , 0 , 0 , 0 , 0
BC Design=,, 0 ,, 0 ,,,,,,
BC HTab HWMax=48.09

Type RM Length L Ch R = 1 ,3333.050,98.78,98.2,97.61
BEGIN DESCRIPTION:
Cross Section Obtained From LIDAR Data, With Channel Interpolated Based on Slope
END DESCRIPTION:
XS GIS Cut Line= 2
     3101983.326    13820441.102     3101649.086    13820438.313
#Sta/Elev= 30
       0    46.6   12.42   46.37   27.42   46.27   46.17   46.03   75.92   46.05
    90.8   45.97  102.42   45.59   110.3   44.84  114.25   44.46  117.43   44.19
  132.43   40.52  135.43   39.63  150.41   37.45  161.33   34.31  162.36   30.73
  168.05   29.92  173.45    30.3  174.44   33.95  183.84   37.21  189.88   41.38
  192.43   42.05  194.93   42.59  207.43   45.07  222.43   46.49  237.43   47.01
  252.43   47.09  267.43   47.01  284.11   47.12  297.43   46.89  334.25   46.79
#Mann= 5 ,-1 , 0
       0      .1       0   110.3     .04       0  150.41    .015       0
  183.84     .04       0  284.11      .1       0
#XS Ineff= 2 , 0
       0  111.89   46.42  216.62       0   46.17
Permanent Ineff=
       F       F
Bank Sta=114.25,207.43
XS Rating Curve= 0
Exp/Cntr=.5,.3

Type RM Length L Ch R = 1 ,3234.850,371.8,372.51,372.79
BEGIN DESCRIPTION:
Survey Data Used for Points from Station 106.81 to 212.46.  All other Points obtained from LIDAR data.
END DESCRIPTION:
XS GIS Cut Line= 2
     3101989.718    13820341.388      3101659.43    13820341.853
#Sta/Elev= 30
       0   47.36   27.08   47.24   40.16   47.36   55.16   47.64  100.16   47.63
  106.81   47.85   112.3   47.09  125.66   45.24  150.64   37.43  151.93   36.96
  160.89    33.7  162.72   29.97  164.19   29.79  167.66   29.72  171.95   29.94
  172.69    30.1  172.84   33.64  181.66   36.32   192.6   39.87  212.46   44.64
  224.28   44.95  235.16   46.06  239.31   46.29  250.16    47.1  275.97   47.52
  280.75   47.71  285.56    47.9  295.16   48.09  314.41    48.2  330.29   48.16
#Mann= 5 ,-1 , 0
       0      .1       0   112.3     .04       0  151.93    .015       0
  181.66     .04       0  280.75      .1       0
Bank Sta=112.3,212.46
XS Rating Curve= 0
Exp/Cntr=.3,.1

Type RM Length L Ch R = 1 ,2862.337,68.17,68.57,69.02
BEGIN DESCRIPTION:
Survey Data Used for Points from Station 126.44 to 190.89.  All other Points obtained from LIDAR data.
END DESCRIPTION:
XS GIS Cut Line= 2
     3101997.969    13819970.889       3101671.4      13819968.1
#Sta/Elev= 30
       0   46.87    3.41   46.82   11.62   46.41   25.32   46.14   41.37   46.37
   67.28   46.24   78.41   46.28   85.99    45.9   93.42   45.41  104.51   43.17
  108.18   42.43  126.44   40.09  140.43   36.06  150.83   33.36  151.66   29.75
  157.93   28.25  162.76   29.02  163.82   32.93  173.38   35.88  176.35   36.68
  190.89   40.62  228.42   45.76  228.61   45.78  237.14   46.54  243.42   46.99
  261.46   47.77  288.42   47.92  303.42   47.57  318.42   47.82  326.58   47.85
#Mann= 5 ,-1 , 0
       0      .1       0  104.51     .04       0  140.43    .015       0
  176.35     .04       0  228.61      .1       0
Bank Sta=93.42,228.42
XS Rating Curve= 0
Exp/Cntr=.5,.3

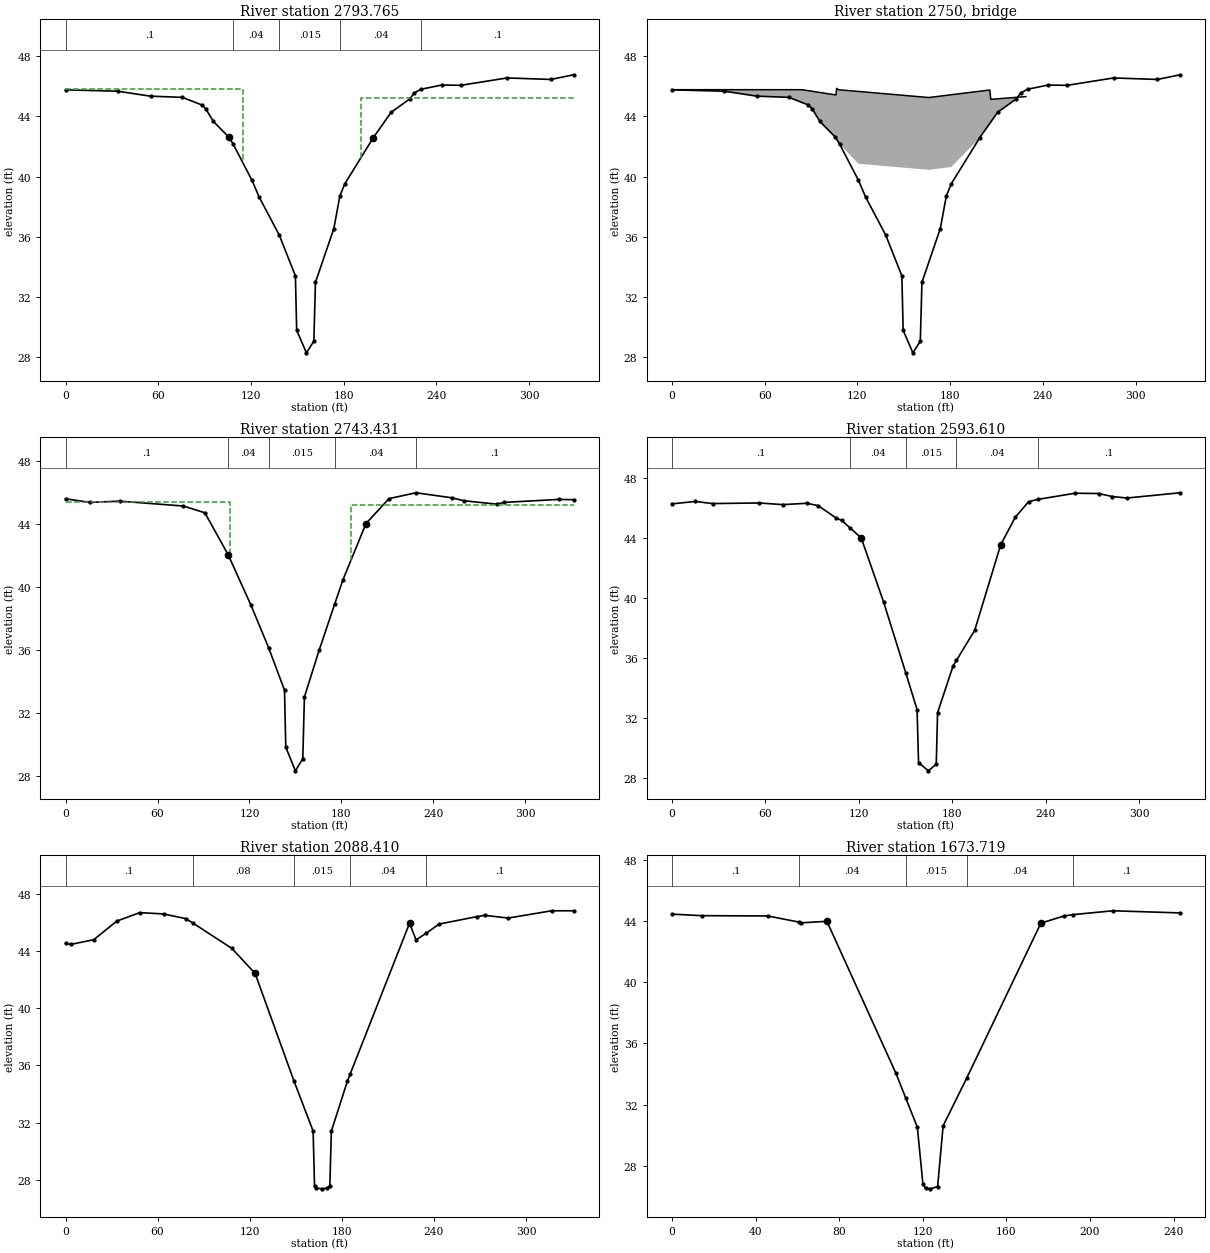
Type RM Length L Ch R = 1 ,2793.765,49.6,50.33,51.11
BEGIN DESCRIPTION:
Cross Section Obtained From LIDAR Data, With Channel Interpolated Based on Slope
END DESCRIPTION:
XS GIS Cut Line= 2
     3102001.572    13819903.483     3101672.911     13819898.37
#Sta/Elev= 30
       0   45.76   33.69   45.67   55.02   45.34   75.68   45.26   88.11   44.76
   90.68   44.51    95.7   43.66  105.68   42.62  108.47   42.16  120.68   39.75
  125.25   38.65  138.34   36.11  148.74   33.41  149.57    29.8  155.84    28.3
  160.67   29.07  161.73   32.98  173.61   36.55   177.5   38.71  180.69   39.52
  199.11   42.58  210.69   44.27  222.64   45.15  225.69   45.56  230.09    45.8
  243.42   46.08   255.7   46.06   285.7   46.55  314.08   46.45   328.7   46.76
#Mann= 5 ,-1 , 0
       0      .1       0  108.47     .04       0  138.34    .015       0
   177.5     .04       0  230.09      .1       0
#XS Ineff= 2 , 0
       0     115   45.81     191       0   45.23
Permanent Ineff=
       F       F
Bank Sta=105.68,199.11
XS Rating Curve= 0
Exp/Cntr=.5,.3

Type RM Length L Ch R = 3 ,2750    ,,,
BEGIN DESCRIPTION:
S17 Glen Haven Road
END DESCRIPTION:
Bridge Culvert--1,0,-1,-1, 0
Deck Dist Width WeirC Skew NumUp NumDn MinLoCord MaxHiCord MaxSubmerge Is_Ogee
.67,49,2.6,0, 9, 9, , , .95, 0, 0,0,,
       0   84.06  106.06  106.58  107.56  166.14  205.65  206.25  228.93
   45.77   45.77   45.42   45.86   45.77   45.25   45.75   45.13   45.31
   40.97   40.97   40.62   41.06   40.97   40.45   40.95   40.33   40.51
       0   84.06  106.06  106.58  107.56  166.14  205.65  206.25  228.93
   45.77   45.77   45.42   45.86   45.77   45.25   45.75   45.13   45.31
   40.97   40.97   40.62   41.06   40.97   40.45   40.95   40.33   40.51
BR Coef=-1 , 1 , 0 ,1.25, 0 ,,,.8,0,2,0,
WSPro=,,,, 1 ,,,, 0 ,,,, 0 ,,,,-1 ,-1 ,-1 , 0 , 0 , 0 , 0 , 0
BC Design=,, 0 ,, 0 ,,,,,,
BC HTab HWMax=46.76

Type RM Length L Ch R = 1 ,2743.431,151.75,149.82,147.88
BEGIN DESCRIPTION:
Cross Section Obtained From LIDAR Data, With Channel Interpolated Based on Slope
END DESCRIPTION:
XS GIS Cut Line= 2
     3102001.804    13819855.137     3101670.586     13819845.84
#Sta/Elev= 25
       0   45.58   15.91   45.35   35.27   45.43   76.94   45.12   90.93   44.69
  106.03   42.04  120.95   38.84  132.43   36.15  142.83   33.45  143.66   29.84
  149.93   28.34  154.76   29.11  155.82   33.02  165.38   35.97  175.61   38.92
  180.97   40.45  195.98   44.01  210.98   45.59  228.63   45.96  252.09   45.64
  260.13   45.45  281.28   45.24  286.01   45.35  321.89   45.54  331.35   45.52
#Mann= 5 ,-1 , 0
       0      .1       0  106.03     .04       0  132.43    .015       0
  175.61     .04       0  228.63      .1       0
#XS Ineff= 2 , 0
       0  107.42   45.39     186       0    45.2
Permanent Ineff=
       F       F
Bank Sta=106.03,195.98
XS Rating Curve= 0
Exp/Cntr=.5,.3

Type RM Length L Ch R = 1 ,2593.610,504.39,505.2,506.13
BEGIN DESCRIPTION:
Survey Data Used for Points from Station 121.45 to 210.98.  All other Points obtained from LIDAR data.
END DESCRIPTION:
XS GIS Cut Line= 2
     3102013.426    13819700.336     3101687.322    13819701.499
#Sta/Elev= 30
       0   46.27   14.97   46.43   26.02   46.29   55.92   46.33    71.2   46.22
   86.56   46.31   93.87   46.15  105.44   45.32  108.87   45.17  114.14   44.68
  121.46      44  135.91    39.7  150.01   35.01  157.32   32.54  158.28      29
   164.6   28.45  169.64    28.9  170.49   32.33  180.47   35.46  182.62   35.83
  194.33   37.83  210.97   43.53  220.33   45.37  228.87   46.41   234.8   46.57
  258.87   46.98  273.87   46.96  282.63   46.76  291.97   46.66  326.11   47.01
#Mann= 5 ,-1 , 0
       0      .1       0  114.14     .04       0  150.01    .015       0
  182.62     .04       0   234.8      .1       0
Bank Sta=121.46,210.97
XS Rating Curve= 0
Exp/Cntr=.3,.1

Type RM Length L Ch R = 1 ,2088.410,268.65,414.69,529.81
BEGIN DESCRIPTION:
Survey Data Used for Points from Station 123.54 to 224.15.  All other Points obtained from LIDAR data.
END DESCRIPTION:
XS GIS Cut Line= 2
     3102027.953    13819197.815     3101696.968    13819194.096
#Sta/Elev= 29
       0   44.53     3.4   44.46   18.41   44.79    33.4   46.09    48.4   46.68
   63.88   46.59    78.4   46.26   82.75   45.97   108.4   44.18  123.54   42.43
  148.95   34.89  161.33   31.42  162.26   27.56  163.36   27.43   167.4   27.38
  170.67   27.43  172.23   27.61  173.21   31.41  183.68   34.91  185.36   35.37
  224.15   45.94  228.41   44.78  235.01   45.24  243.41   45.88  267.86    46.4
  273.41   46.49  288.41    46.3  316.75   46.81  331.01   46.81
#Mann= 5 ,-1 , 0
       0      .1       0   82.75     .08       0  148.95    .015       0
  185.36     .04       0  235.01      .1       0
Bank Sta=123.54,224.15
XS Rating Curve= 0
Exp/Cntr=.3,.1

Type RM Length L Ch R = 1 ,1673.719,340.22,336.13,331.98
BEGIN DESCRIPTION:
Survey Data Used for Points from Station 74.13 to 176.51.  All other Points obtained from LIDAR data.
END DESCRIPTION:
XS GIS Cut Line= 2
     3102080.715    13819106.236     3102154.862    13818874.733
#Sta/Elev= 20
       0   44.47   14.34   44.37   45.84   44.35   60.77   43.95   61.77    43.9
   74.13      44  107.12   34.06  111.82   32.44   117.4   30.52  120.09   26.78
  121.35   26.53  123.67   26.48  127.11   26.63  129.74   30.61  140.99   33.72
  176.51   43.88  187.59   44.35  192.04   44.44  210.96   44.69  243.09   44.55
#Mann= 5 ,-1 , 0
       0      .1       0   60.77     .04       0  111.82    .015       0
  140.99     .04       0  192.04      .1       0
Bank Sta=74.13,176.51
XS Rating Curve= 0
Exp/Cntr=.3,.1