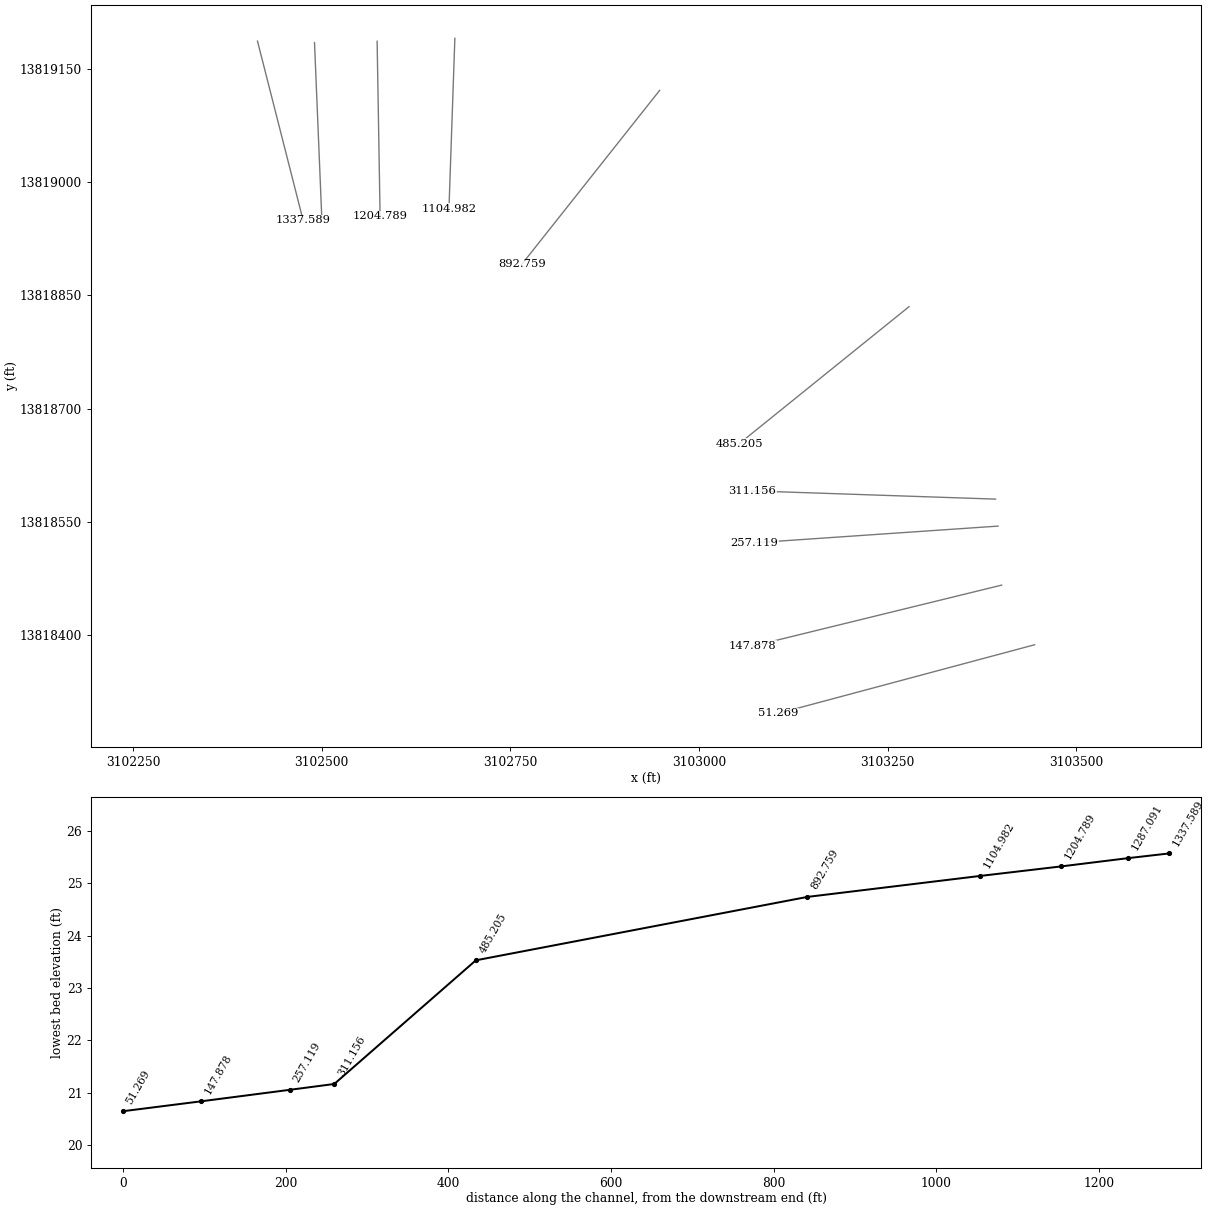
HEC-RAS study D111-00-00.prj: D111-00-00

--- D111-00-00.g01 (geometry) --- (continued)

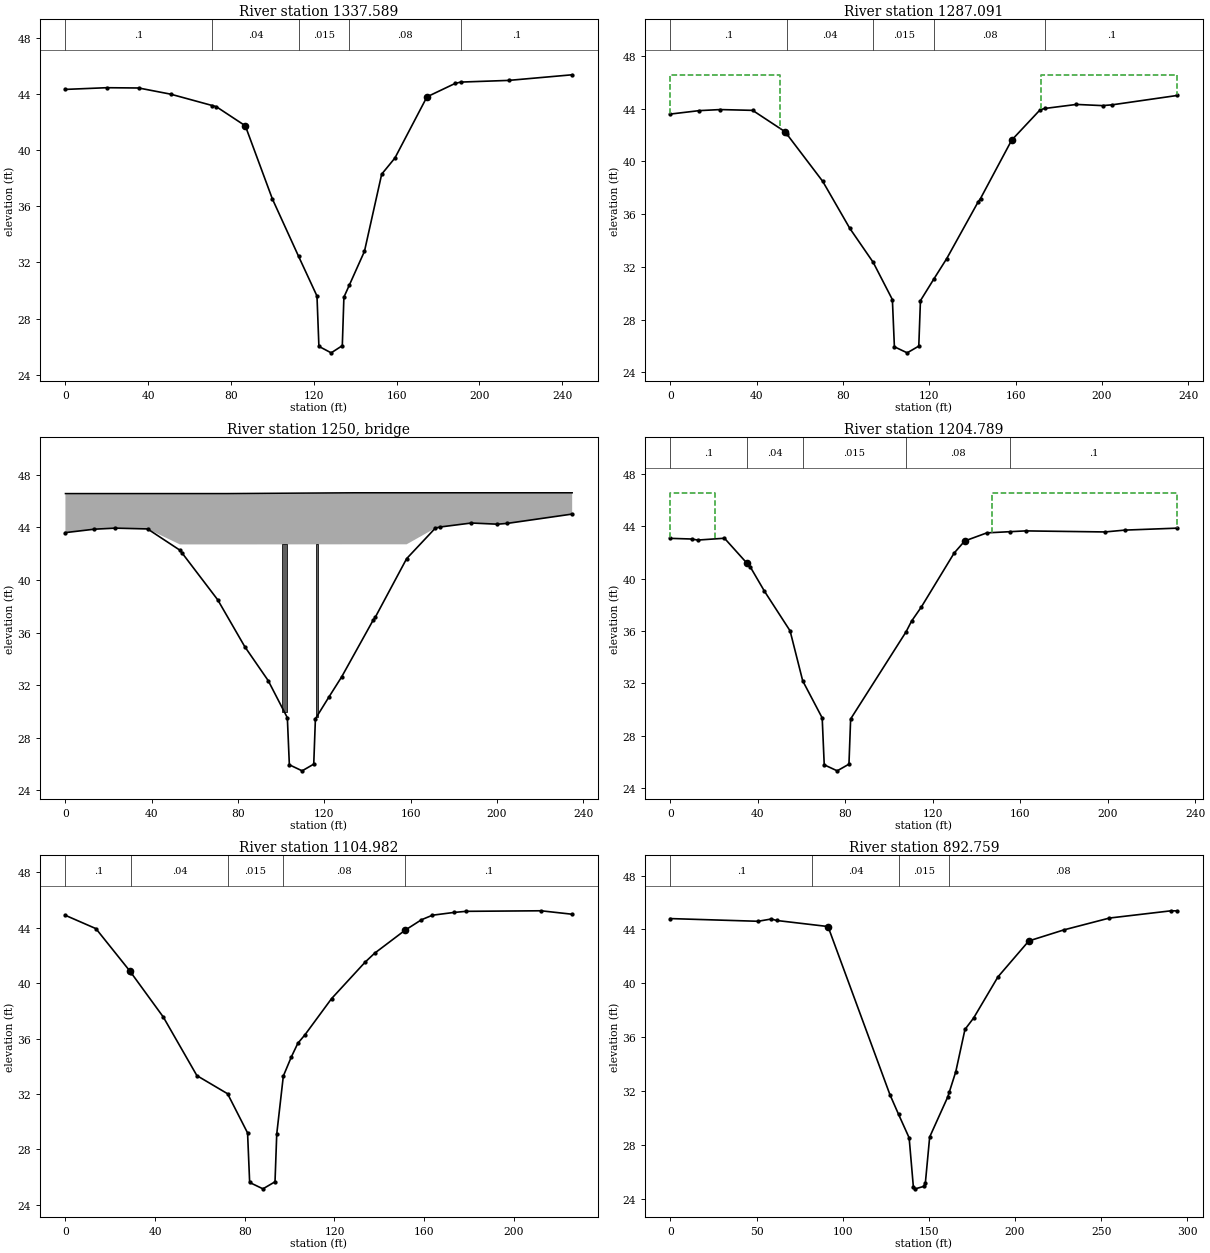
Type RM Length L Ch R = 1 ,1337.589,64.63,50.5,37.61
BEGIN DESCRIPTION:
Survey Data Used for Points from Station 72.91 to 152.83.  All other Points obtained from LIDAR data.
END DESCRIPTION:
XS GIS Cut Line= 2
     3102414.955    13819186.891     3102475.388    13818949.576
#Sta/Elev= 23
       0   44.31   19.93   44.43    35.4   44.41   50.88   43.97   71.02   43.16
   72.91   43.08   86.93   41.72     100   36.52  112.65   32.44  121.56   29.61
  122.49   26.03  128.42   25.57   133.8   26.08  134.57   29.53  137.14   30.37
   144.5   32.79  152.83   38.28  159.23   39.43  174.71   43.78  188.27   44.73
  191.01   44.83  214.19   44.95  244.89   45.35
#Mann= 5 ,-1 , 0
       0      .1       0   71.02     .04       0  112.65    .015       0
  137.14     .08       0  191.01      .1       0
Bank Sta=86.93,174.71
XS Rating Curve= 0
Exp/Cntr=.5,.3

Type RM Length L Ch R = 1 ,1287.091,84.24,82.3,81.2
BEGIN DESCRIPTION:
Cross Section Obtained From LIDAR Data, With Channel Interpolated Based on Slope
END DESCRIPTION:
XS GIS Cut Line= 2
     3102490.496    13819185.031     3102500.258    13818950.273
#Sta/Elev= 25
       0    43.6   13.37   43.86   23.08   43.94   38.09   43.88   53.11   42.26
   54.04   42.06    70.6   38.49   83.13   34.93   93.98   32.35  102.89   29.52
  103.82   25.94  109.75   25.48  115.13   25.99   115.9   29.44  122.18    31.1
  128.08   32.63  142.67   36.94  143.75   37.19   158.2   41.62  171.49   43.94
  173.87   44.03  188.22   44.33  200.32   44.24  204.79    44.3  234.96   45.01
#Mann= 5 ,-1 , 0
       0      .1       0   54.04     .04       0   93.98    .015       0
  122.18     .08       0  173.87      .1       0
#XS Ineff= 2 , 0
       0      51   46.55     172       0   46.58
Permanent Ineff=
       F       F
Bank Sta=53.11,158.2
XS Rating Curve= 0
Exp/Cntr=.5,.3

Type RM Length L Ch R = 3 ,1250    ,,,
Bridge Culvert--1,0,-1,-1, 0
Deck Dist Width WeirC Skew NumUp NumDn MinLoCord MaxHiCord MaxSubmerge Is_Ogee
11,60,2.6,0, 4, 4, , , .95, 0, 0,0,,
       0      75     134  234.96
   46.57   46.57   46.63   46.63
    42.7    42.7   42.71   42.71
       0      57     116  231.77
   46.56   46.56   46.58   46.58
   42.72   42.72   42.68   42.68
Pier Skew, UpSta & Num, DnSta & Num=  ,101.5, 4 ,68, 4 , 0 , 0 , 0 ,,
       2       2       1       1
      25      32   32.01      45
       2       2       1       1
      25      32   32.01      45
Pier Skew, UpSta & Num, DnSta & Num=  ,116.5, 2 ,83, 2 , 0 , 0 , 0 ,,
       1       1
      25      45
       1       1
      25      45
BR Coef=-1 , 1 , 1 ,1.25, 0 ,,,.8,0,2,0,
WSPro=,,,, 1 ,,,, 0 ,,,, 0 ,,,,-1 ,-1 ,-1 , 0 , 0 , 0 , 0 , 0
BC Design=,, 0 ,, 0 ,,,,,,
BC HTab HWMax=45.01

Type RM Length L Ch R = 1 ,1204.789,103.79,99.81,96.74
BEGIN DESCRIPTION:
Cross Section Obtained From LIDAR Data, With Channel Interpolated Based on Slope
END DESCRIPTION:
XS GIS Cut Line= 2
     3102573.475    13819186.658     3102577.426    13818954.922
#Sta/Elev= 25
       0   43.07    9.69   43.02   12.47   42.94   24.69   43.08   34.77   41.21
    36.5   40.89      43   39.03    54.7   36.01   60.4832.19221   69.3929.36221
   70.3225.78221   76.2525.32221   81.6325.83221    82.429.28221  107.77   35.94
  110.26   36.75   114.7   37.82  129.71   41.94  134.57   42.87  144.71   43.49
  155.29   43.58  162.38   43.64  198.76   43.56  207.78    43.7  231.77   43.85
#Mann= 5 ,-1 , 0
       0      .1       0   34.77     .04       0   60.48    .015       0
  107.77     .08       0  155.29      .1       0
#XS Ineff= 2 , 0
       0   20.46   46.55     147       0   46.55
Permanent Ineff=
       F       F
Bank Sta=34.77,134.57
XS Rating Curve= 0
Exp/Cntr=.5,.3

Type RM Length L Ch R = 1 ,1104.982,264.37,212.22,175.3
BEGIN DESCRIPTION:
Cross Section Obtained From LIDAR Data, With Channel Interpolated Based on Slope
END DESCRIPTION:
XS GIS Cut Line= 2
     3102676.485    13819190.564     3102668.655     13818964.69
#Sta/Elev= 26
       0    44.9    13.6   43.94   28.61    40.9   29.38   40.73   43.62   37.56
   58.63   33.32   72.32   32.01   81.23   29.18   82.16    25.6   88.09   25.14
   93.47   25.65   94.24    29.1   97.18   33.29  100.75   34.67  103.66   35.66
  106.78   36.26  118.67   38.88  133.67   41.52  137.87   42.16  151.43   43.82
  158.77   44.58  163.69   44.91  173.28   45.11   178.7   45.19  212.11   45.23
  226.01   44.98
#Mann= 5 ,-1 , 0
       0      .1       0   29.38     .04       0   72.32    .015       0
   97.18     .08       0  151.43      .1       0
Bank Sta=28.61,151.43
XS Rating Curve= 0
Exp/Cntr=.3,.1

Type RM Length L Ch R = 1 ,892.759 ,424.12,407.55,396.29
BEGIN DESCRIPTION:
Survey Data Used for Points from Station 91.46 to 165.63.  All other Points obtained from LIDAR data.
END DESCRIPTION:
XS GIS Cut Line= 2
     3102947.809    13819121.577     3102765.116    13818891.003
#Sta/Elev= 24
       0   44.81   50.83   44.61   58.55   44.78    61.6   44.67   91.46   44.22
  127.38   31.74  132.38   30.28  138.55   28.53  141.01   24.87  142.08   24.74
  146.99   24.92  147.94   25.14  150.47   28.59  160.95   31.56   161.8    31.9
  165.63   33.44  170.96   36.58     176   37.43   190.1   40.48  208.03   43.15
  228.37   43.97  254.82   44.85  290.71   45.39  294.18   45.38
#Mann= 4 ,-1 , 0
       0      .1       0   82.37     .04       0  132.38    .015       0
   161.8     .08       0
Bank Sta=91.46,208.03
XS Rating Curve= 0
Exp/Cntr=.3,.1

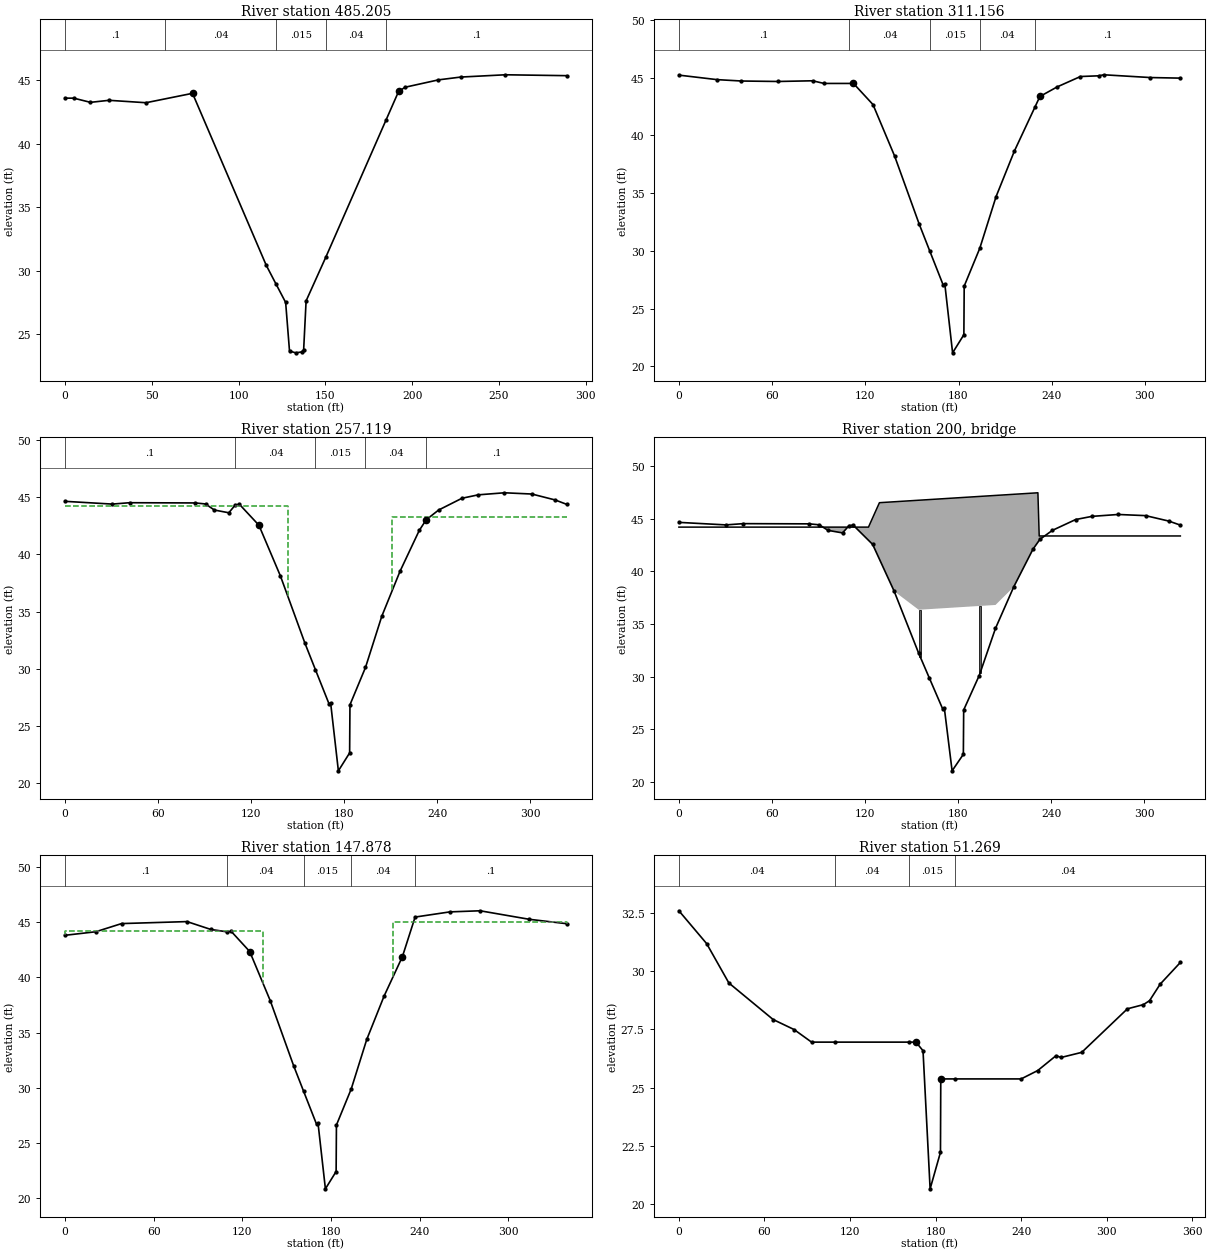
Type RM Length L Ch R = 1 ,485.205 ,230.16,174.05,140.55
BEGIN DESCRIPTION:
Survey Data Used for Points from Station 73.39  to 192.15.  All other Points obtained from LIDAR data.
END DESCRIPTION:
XS GIS Cut Line= 2
     3103278.319    13818835.052     3103053.433    13818653.592
#Sta/Elev= 22
       0   43.58    4.91   43.58   14.58   43.25   25.24   43.41   46.58   43.22
   73.39   43.96  115.88   30.42  121.37   28.98  127.05    27.5  129.28   23.67
  132.88   23.53  136.25    23.6  137.43   23.78  138.84   27.62  150.26   31.08
  184.94   41.87  192.15   44.11  195.92   44.44  215.12   45.02  227.92   45.24
  253.67   45.42  288.97   45.35
#Mann= 5 ,-1 , 0
       0      .1       0   57.79     .04       0  121.37    .015       0
  150.26     .04       0  184.94      .1       0
Bank Sta=73.39,192.15
XS Rating Curve= 0
Exp/Cntr=.3,.1

Type RM Length L Ch R = 1 ,311.156 ,46.45,54.04,58.31
BEGIN DESCRIPTION:
Survey Data Used for Points from Station 112.38 to 232.38.  All other Points obtained from LIDAR data.
END DESCRIPTION:
XS GIS Cut Line= 2
     3103392.919    13818580.007     3103070.301    13818590.931
#Sta/Elev= 27
       0   45.22   24.54   44.83   40.28   44.71   63.81   44.67   86.08   44.73
   93.42    44.5  112.38    44.5  124.94   42.67  138.84   38.22  154.63   32.34
   161.4   30.02  170.17   27.03  171.21    27.1  176.19   21.17  183.45   22.74
  183.66   26.95  193.68   30.22  204.18    34.7  215.95   38.64  229.19   42.45
  232.38   43.37   243.5    44.2  258.51    45.1  270.23   45.16  273.52   45.25
  303.54   45.01   322.8   44.96
#Mann= 5 ,-1 , 0
       0      .1       0  109.75     .04       0   161.4    .015       0
  193.68     .04       0  229.19      .1       0
Bank Sta=112.38,232.38
XS Rating Curve= 0
Exp/Cntr=.5,.3

Type RM Length L Ch R = 1 ,257.119 ,97.22,109.24,117.94
BEGIN DESCRIPTION:
Cross Section Obtained From LIDAR Data, With Channel Interpolated Based on Slope
END DESCRIPTION:
XS GIS Cut Line= 2
     3103396.191     13818544.25     3103073.555    13818522.131
#Sta/Elev= 30
       0   44.65   30.36   44.41    41.5   44.53   83.94   44.51    90.5   44.42
   96.21   43.89  105.53   43.65  109.75   44.34  112.38   44.39  124.94   42.56
  138.84   38.11  154.63   32.23   161.4   29.91  170.17   26.92  171.21   26.99
  176.19   21.06  183.45   22.63  183.66   26.84  193.68   30.11  204.18   34.59
  215.95   38.53  228.34    42.1  232.84   43.04  240.85   43.89  255.89   44.92
  266.38   45.22  283.32    45.4  300.99   45.29  316.03   44.77  323.39   44.39
#Mann= 5 ,-1 , 0
       0      .1       0  109.75     .04       0   161.4    .015       0
  193.68     .04       0  232.84      .1       0
#XS Ineff= 2 , 0
       0  143.83    44.2     211       0   43.31
Permanent Ineff=
       F       F
Bank Sta=124.94,232.84
XS Rating Curve= 0
Exp/Cntr=.5,.3

Type RM Length L Ch R = 3 ,200     ,,,
BEGIN DESCRIPTION:
S21 Braeswood
END DESCRIPTION:
Bridge Culvert--1,0,-1,-1, 0
Deck Dist Width WeirC Skew NumUp NumDn MinLoCord MaxHiCord MaxSubmerge Is_Ogee
17,75,2.6,0, 6, 5, , , .95, 0, 0,0,,
       0  122.25  129.32  231.53  232.37  323.39
    44.2    44.2   46.52   47.46   43.36   43.36
    33.8    33.8   36.12   37.06      20      20
       0  122.25  129.32  231.53  232.37
    44.2    44.2   46.52   47.46   43.36
    33.8    33.8   36.12   37.06      20
Pier Skew, UpSta & Num, DnSta & Num=  ,155.6, 2 ,155.6, 2 , 0 , 0 , 0 ,,
       1       1
      20   37.06
       1       1
      20   37.06
Pier Skew, UpSta & Num, DnSta & Num=  ,194.2, 2 ,194.2, 2 , 0 , 0 , 0 ,,
       1       1
      20   37.06
       1       1
      20   37.06
BR Coef=-1 , 1 , 1 ,1.25, 0 ,,,.8,-1,2,0,
WSPro=,,,, 1 ,,,, 0 ,,,, 0 ,,,,-1 ,-1 ,-1 , 0 , 0 , 0 , 0 , 0
BC Design=,, 0 ,, 0 ,,,,,,
BC HTab HWMax=45.4

Type RM Length L Ch R = 1 ,147.878 ,93.71,96.61,95.15
BEGIN DESCRIPTION:
Cross Section Obtained From LIDAR Data, With Channel Interpolated Based on Slope
END DESCRIPTION:
XS GIS Cut Line= 2
     3103401.025    13818466.056      3103071.26    13818385.286
#Sta/Elev= 25
       0   43.81   20.71   44.13   38.19   44.87   82.49   45.05   98.58   44.34
  109.75   44.12  112.38   44.17  124.94   42.34  138.84   37.89  154.63   32.01
   161.4   29.69  170.17    26.7  171.21   26.77  176.19   20.84  183.45   22.41
  183.66   26.62  193.68   29.89  204.18   34.37  215.95   38.31  228.34   41.88
  236.92   45.46  260.48   45.93  280.93   46.03  314.14   45.26  339.51   44.86
#Mann= 5 ,-1 , 0
       0      .1       0  109.75     .04       0   161.4    .015       0
  193.68     .04       0  236.92      .1       0
#XS Ineff= 2 , 0
       0     134   44.24  221.99       0   44.97
Permanent Ineff=
       F       F
Bank Sta=124.94,228.34
XS Rating Curve= 0
Exp/Cntr=.5,.3

Type RM Length L Ch R = 1 ,51.269  ,51.43,51.27,60.58
BEGIN DESCRIPTION:
Cross Section Obtained From LIDAR Data
END DESCRIPTION:
XS GIS Cut Line= 2
     3103444.756    13818387.056     3103105.043    13818296.105
#Sta/Elev= 24
       0   32.59   19.46   31.18   35.04   29.49    66.1   27.92   80.79   27.49
   93.04   26.95  109.75   26.95   161.4   26.95  166.28   26.95  171.21   26.58
  176.19   20.65  183.45   22.22  183.66   25.37  193.68   25.37  240.03   25.37
  251.67   25.73  264.53   26.37  267.97   26.29  282.51   26.51  314.55   28.38
  325.77   28.56  330.08   28.73  337.54   29.44  351.68   30.37
#Mann= 4 ,-1 , 0
       0     .04       0  109.75     .04       0   161.4    .015       0
  193.68     .04       0
Bank Sta=166.28,183.66
XS Rating Curve= 0
Exp/Cntr=.3,.1

Chan Stop Cuts=-1